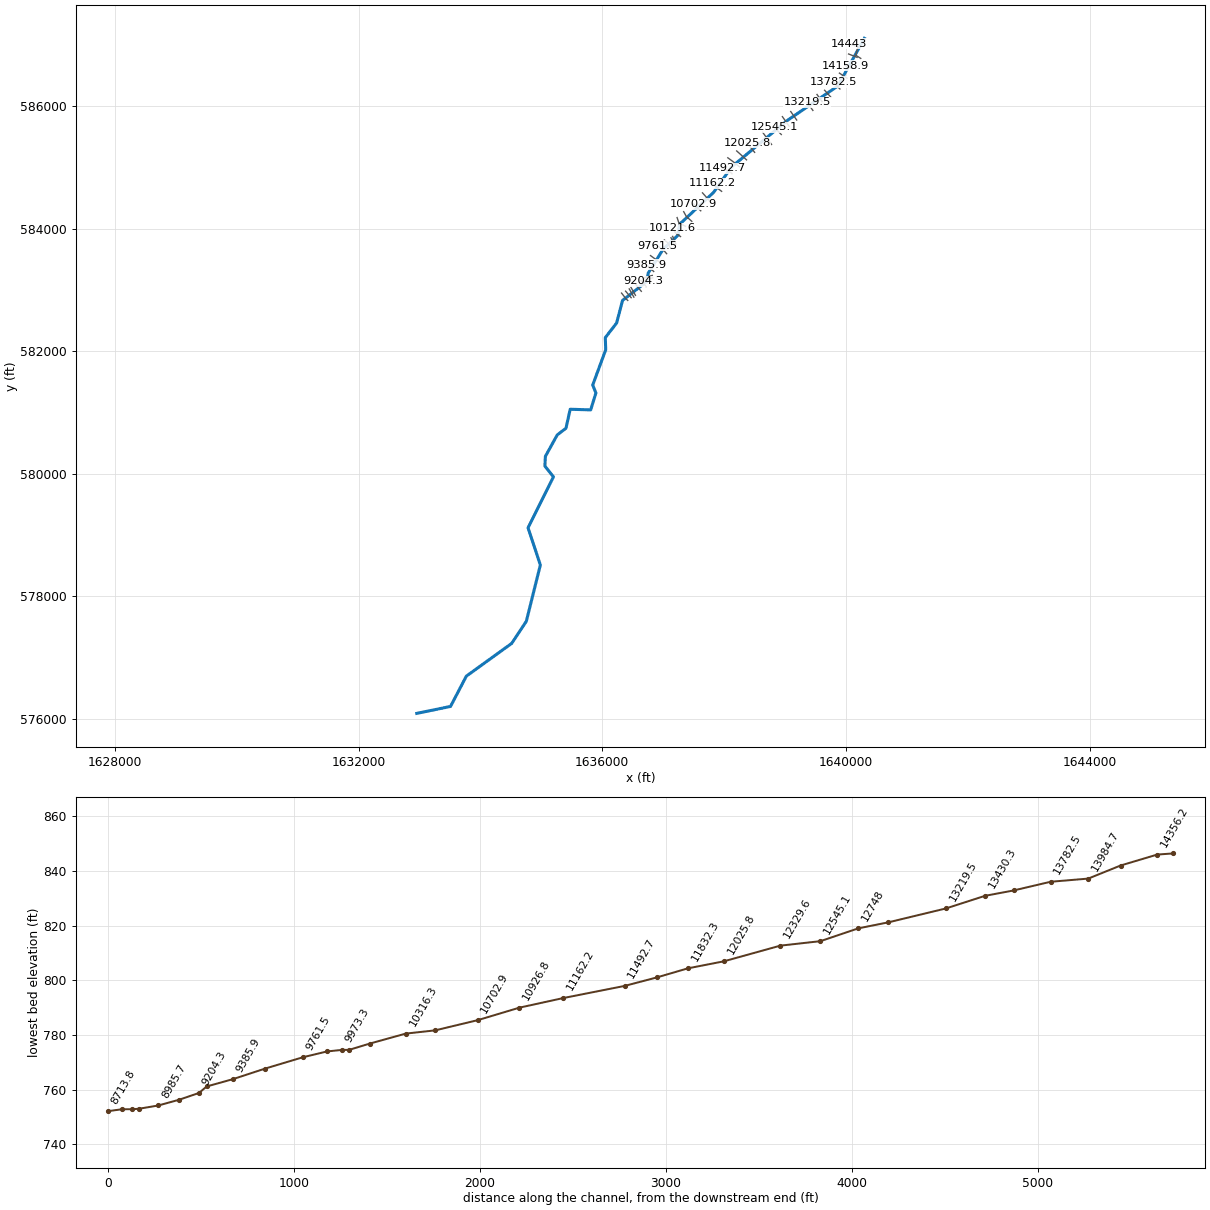
--- LONGRUN.prj (project) ---

Proj Title=LONGRUN
Current Plan=p01
Default Exp/Contr=0,0
English Units
Geom File=g01
Flow File=f01
Plan File=p01
BEGIN DESCRIPTION:
END DESCRIPTION:
DSS Export Rating Curves= 0
DSS Export Rating Curve Sorted= 0
DSS Export Volume Flow Curves= 0
DXF OffsetX= 0
DXF OffsetY= 0
DXF ScaleX= 0
DXF ScaleY= 0

--- LONGRUN.p01 (plan) ---

Plan Title=Floodplain
Program Version=4.00
Geom File=g01
Flow File=f01
K Sum by GR=0
Std Step Tol=0.01
Critical Tol=0.01
Num of Std Step Trials=20
Max Error Tol=0.3
Flow Tol Ratio=0.001
Split Flow NTrial=30
Split Flow Tol=0.02
Split Flow Ratio=0.02
Log Output Level=0
Friction Slope Method=1
Unsteady Friction Slope Method=2
Unsteady Bridges Friction Slope Method=1
Global Log Level=0
CheckData=False
Run HTab=0
Run UNet=0
Run PostProcess=0
UNET Theta=0
UNET Theta Warmup=0
UNET ZTol=0
UNET ZSATol=0
UNET MxIter=0
UNET MaxInSteps=0
UNET DtIC=0
UNET DtMin=0
UNET MaxCRTS=0
UNET WFStab=0
UNET SFStab=0
UNET WFX=0
UNET SFX=0
UNET DSS MLevel=0
UNET DZMax Abort=0
UNET Convert EG Bridges=0
UNET Use Existing IB Tables=0
UNET Froude Limit=0
UNET Froude Power=0
Write IC File=0
Echo Input=False
Echo Output=False
Write Detailed=0

--- LONGRUN.f01 (steady flow) ---

Flow Title=NFF Regression Equation
Program Version=4.10
Number of Profiles= 1
Profile Names=P100yr
River Rch & RM=LONGRUN,Main            ,14443
937.8314
River Rch & RM=LONGRUN,Main            ,12025.8
1093.948
River Rch & RM=LONGRUN,Main            ,8713.8
1196.326
River Rch & RM=LONGRUN,Main            ,8312.8
1287.852
River Rch & RM=LONGRUN,Main            ,7236.6
1345.676
River Rch & RM=LONGRUN,Main            ,6591.6
1849.172
River Rch & RM=LONGRUN,Main            ,2620.9
1942.522
Boundary for River Rch & Prof#=LONGRUN,Main            , 1
Up Type= 0
Dn Type= 3
Dn Slope=0.009
DSS Import GetInterval= 0
DSS Import GetPeak= 0
DSS Import FillOption= 0

--- LONGRUN.g01 (geometry) ---

Geom Title=USGS 10m DEM
Program Version=4.10

River Reach=LONGRUN         ,Main
Reach XY= 30
      1640301.14      587111.853     1639864.646      586332.886
     1639026.104      585763.442     1638120.249      585009.496
     1637827.017      584596.228     1637270.896       584076.81
     1637238.778      583891.914     1637001.798      583672.296
     1636752.666      583276.463     1636735.305      583144.518
     1636332.528       582831.15     1636235.305      582462.227
     1636049.541      582223.511     1636056.486      582025.595
     1635843.378      581449.727     1635895.462      581319.518
     1635809.823       581043.22     1635473.587      581053.893
     1635404.576      580743.997     1635260.925      580634.625
     1635066.698      580284.148     1635058.017      580125.728
     1635198.847      579949.727      1634782.18      579117.695
     1634984.003      578509.622     1634753.535      577590.352
     1634513.951      577229.675      1633769.16      576694.518
     1633510.045      576199.727      1632956.66      576086.445

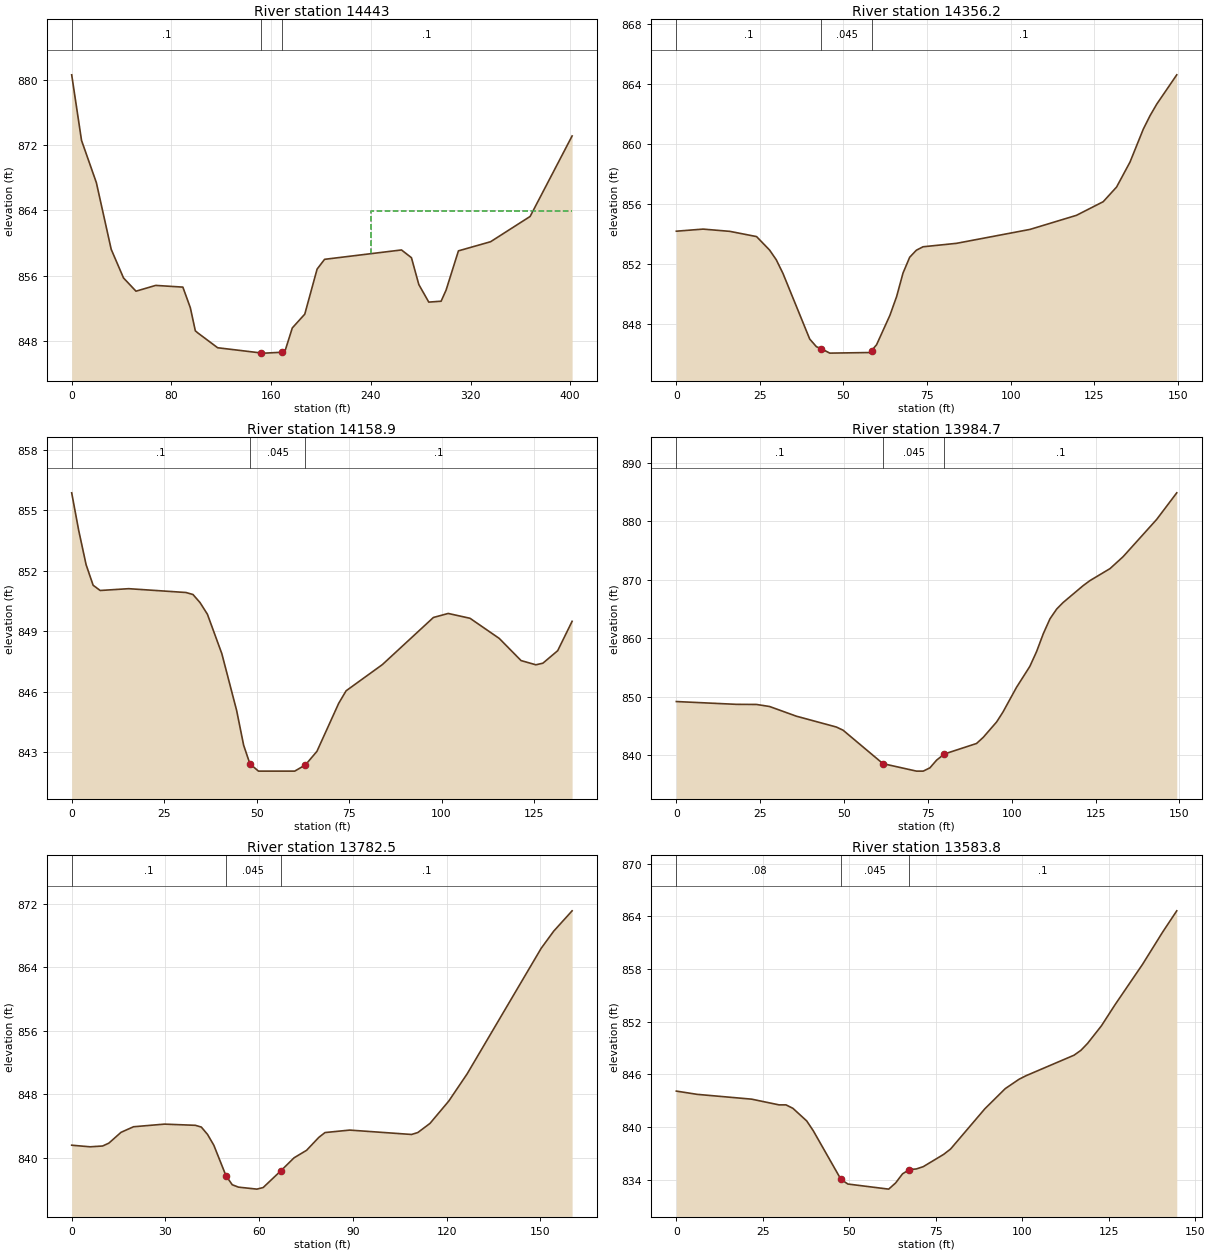
Type RM Length L Ch R = 1 ,14443   ,23.7,86.8,124.6
XS GIS Cut Line= 4
     1640241.179      586784.241     1640157.644      586837.685
     1640197.619        586973.6     1640044.565      587022.522
#Sta/Elev= 30
       0  880.63     7.9  872.58    19.8   867.4    31.7  859.22    41.6   855.7
    51.6  854.08    67.4  854.79    89.2  854.58    95.2  852.05    99.2  849.22
   101.2  848.96   117.1  847.14   151.9   846.5     155  846.48     169  846.59
     171  846.66     177  849.57     187  851.26   196.9  856.79   202.9  857.99
   264.6  859.14   272.6  858.19   278.5   854.9   286.5  852.74   296.4  852.85
   300.4  854.22   310.3  859.03   336.1  860.15   367.8  863.25   401.5  873.13
#Mann= 3 , 0 , 0
       0      .1       0   151.9    .045       0     169      .1       0
#XS Ineff= 2 , 0
                          240.48          863.88
Permanent Ineff=
       F       F
Bank Sta=151.9,169
XS Rating Curve= 0 ,0
Exp/Cntr=0.3,0.1

Type RM Length L Ch R = 1 ,14356.2 ,197.4,197.3,196.9
XS GIS Cut Line= 2
     1640180.936      586801.515     1640041.613      586856.202
#Sta/Elev= 30
       0   854.2       8  854.34      16  854.19      24  853.84    27.9  852.94
    29.9  852.29    31.9  851.38    39.9     847    41.9  846.49    43.4  846.35
    45.9  846.06    57.9   846.1    58.4  846.23    59.9  846.62    63.9  848.59
    65.9  849.84    67.8   851.4    69.8  852.46    71.8  852.93    73.8  853.16
    83.8  853.39   105.8  854.32   119.7  855.26   127.7  856.17   131.7  857.15
   135.7  858.81   139.7  861.02   141.7  861.91   143.7  862.68   149.7  864.64
#Mann= 3 , 0 , 0
       0      .1       0    43.4    .045       0    58.4      .1       0
Bank Sta=43.4,58.4
XS Rating Curve= 0 ,0
Exp/Cntr=0.3,0.1

Type RM Length L Ch R = 1 ,14158.9 ,178,174.1,169.2
XS GIS Cut Line= 3
     1640113.228      586619.223     1640078.072       586629.64
     1639986.926        586667.4
#Sta/Elev= 30
       0  855.87     1.9     854     3.9   852.3     5.8  851.28     7.7  851.02
    15.4  851.11    30.9  850.92    32.8  850.82    34.7  850.42    36.7  849.84
    40.6  847.88    44.6  845.06    46.5  843.33    48.2  842.41    50.5  842.05
    60.3  842.05    63.2  842.36    66.3  843.03    72.2  845.42    74.2  846.04
      84  847.34    97.8  849.68   101.8  849.88   107.7  849.64   115.6  848.64
   121.5  847.54   125.5  847.33   127.4  847.41   131.4  848.03   135.3  849.49
#Mann= 3 , 0 , 0
       0      .1       0    48.2    .045       0    63.2      .1       0
Bank Sta=48.2,63.2
XS Rating Curve= 0 ,0
Exp/Cntr=0.3,0.1

Type RM Length L Ch R = 1 ,13984.7 ,207.3,202.2,197.5
XS GIS Cut Line= 2
     1640015.572      586460.369     1639891.874      586543.702
#Sta/Elev= 30
       0  849.17    17.9  848.69    23.9  848.67    27.8  848.32    35.8  846.66
    47.7  844.81    49.7  844.27    61.6  838.54    71.6  837.26    73.6  837.26
    75.6  837.82    77.6  839.14    79.9  840.19    89.5  841.99    91.5  843.04
    95.5  845.68    97.4  847.39   101.4  851.58   105.4  855.19   107.4  857.71
   109.4  860.77   111.4  863.33   113.4     865   115.3  866.11   121.3  869.01
   123.3  869.86   129.3  871.92   133.2  873.96   143.2  880.33   149.2  884.89
#Mann= 3 , 0 , 0
       0      .1       0    61.6    .045       0    79.9      .1       0
Bank Sta=61.6,79.9
XS Rating Curve= 0 ,0
Exp/Cntr=0.3,0.1

Type RM Length L Ch R = 1 ,13782.5 ,199.2,198.7,197.9
XS GIS Cut Line= 2
     1639899.686      586284.588     1639787.707      586399.171
#Sta/Elev= 30
       0  841.62     5.9  841.42     9.9  841.52    11.9  841.88    15.8  843.24
    19.8  843.94    29.7  844.27    39.6  844.12    41.5   843.9    43.5  842.97
    45.5  841.62    49.4  837.78    51.4  836.65    53.4  836.35    59.3   836.1
    61.3   836.3    66.9  838.38    71.2  840.04    75.2  840.98    79.1   842.6
    81.1  843.21      89  843.52   108.8  842.97   110.8  843.21   114.7  844.36
   120.7  847.16   126.6  850.59   150.3  866.37   154.3  868.52   160.2  871.08
#Mann= 3 , 0 , 0
       0      .1       0    49.4    .045       0    66.9      .1       0
Bank Sta=49.4,66.9
XS Rating Curve= 0 ,0
Exp/Cntr=0.3,0.1

Type RM Length L Ch R = 1 ,13583.8 ,155.9,153.6,150.5
XS GIS Cut Line= 2
      1639746.04      586156.984     1639648.384      586263.754
#Sta/Elev= 30
       0  844.09       6  843.72    21.8  843.17    29.7  842.52    31.7  842.52
    33.7  842.13    37.7  840.69    39.6  839.57    47.6  834.03    49.6   833.5
    61.4  832.92    63.4  833.62    65.4  834.66    67.4  835.15    69.4  835.22
    71.4  835.48    77.3  836.88    79.3  837.49    89.2  842.07    95.1  844.37
    99.1  845.44   101.1  845.84     115  848.18     117  848.74   118.9  849.52
   122.9  851.52   126.9  853.96   134.8  858.53   140.7  862.26   144.7  864.63
#Mann= 3 , 0 , 0
       0     .08       0    47.6    .045       0    67.4      .1       0
Bank Sta=47.6,67.4
XS Rating Curve= 0 ,0
Exp/Cntr=0.3,0.1

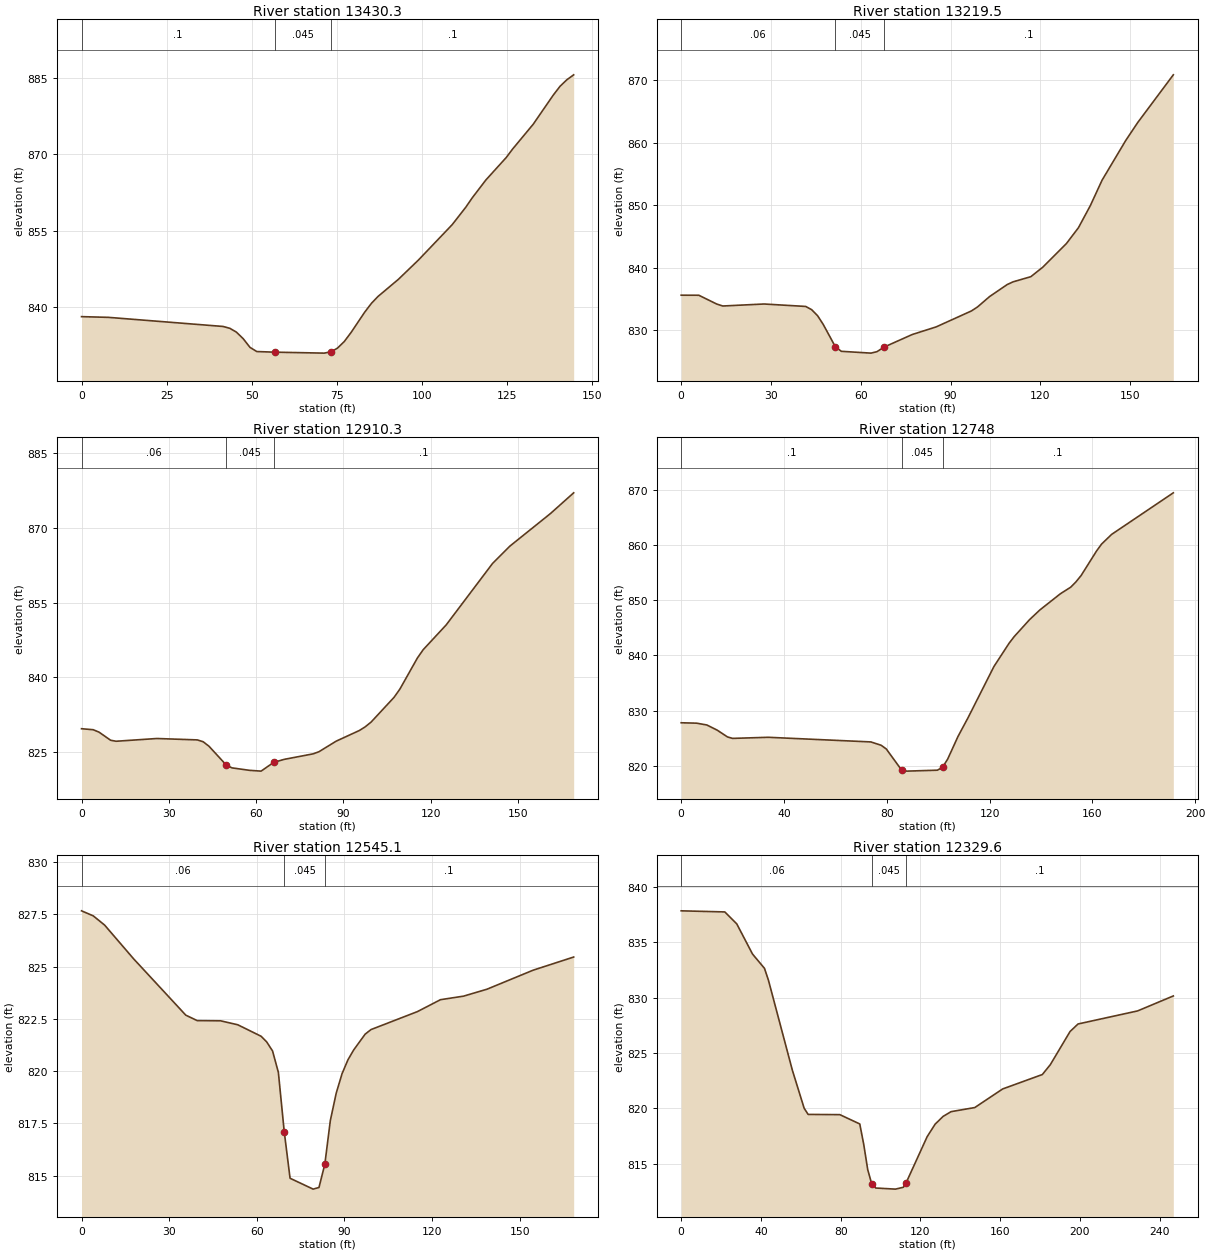
Type RM Length L Ch R = 1 ,13430.3 ,210.9,210.8,210.5
XS GIS Cut Line= 2
     1639608.019      586077.556     1639523.384      586194.744
#Sta/Elev= 30
       0  838.13     7.9  837.99    41.6   836.2    43.6  835.83    45.5  835.09
    47.5   833.8    49.5  832.09    51.5  831.27    56.7  831.15    71.3  830.96
    73.3  831.22    75.2  831.94    77.2  833.24    79.2  835.02    83.2  839.01
    85.2  840.76    87.1  842.09    93.1  845.46      99  849.26   108.9   856.2
   112.9  859.63   114.8  861.48   118.8  864.98   124.8  869.41   126.7   871.1
   132.7  875.93   138.6  881.66   140.6   883.4   142.6  884.68   144.6  885.65
#Mann= 3 , 0 , 0
       0      .1       0    56.7    .045       0    73.3      .1       0
Bank Sta=56.7,73.3
XS Rating Curve= 0 ,0
Exp/Cntr=0.3,0.1

Type RM Length L Ch R = 1 ,13219.5 ,309.1,309.2,309.1
XS GIS Cut Line= 2
     1639455.676      585934.327     1639360.624      586068.442
#Sta/Elev= 30
       0   835.6     5.9  835.59    11.9  834.18    13.9  833.87    27.7  834.19
    41.6   833.8    43.6  833.28    45.6   832.3    47.5  830.89    51.5  827.35
    53.5  826.62    63.4  826.33    65.4  826.56    67.8   827.3    77.2  829.31
    85.2  830.53      97  833.09      99  833.72     103  835.37   108.9   837.3
   110.9  837.74   116.8  838.56   120.8  840.08   128.7  843.87   132.7  846.39
   136.7  849.95   140.6     854   148.5  860.35   152.5  863.22   164.4  870.86
#Mann= 3 , 0 , 0
       0     .06       0    51.5    .045       0    67.8      .1       0
Bank Sta=51.5,67.8
XS Rating Curve= 0 ,0
Exp/Cntr=0.3,0.1

Type RM Length L Ch R = 1 ,12910.3 ,162.3,162.2,162.4
XS GIS Cut Line= 2
     1639190.051      585778.077     1639092.394      585916.098
#Sta/Elev= 30
       0  829.74       4  829.54       6  829.06      10  827.43    11.9  827.23
    25.9  827.78    39.8   827.5    41.8  827.13    43.8  826.23    49.7  822.49
    51.7   821.9    57.7  821.41    61.7  821.25      66  822.99    69.6   823.6
    79.6  824.71    81.6  825.14    87.5  827.25    95.5  829.39    97.5  830.13
    99.5  831.07   107.4  836.03   109.4  837.68   115.4  843.89   117.4  845.56
   125.3  850.52   141.2   862.8   147.2   866.3   161.1   872.8   169.1  876.96
#Mann= 3 , 0 , 0
       0     .06       0    49.7    .045       0      66      .1       0
Bank Sta=49.7,66
XS Rating Curve= 0 ,0
Exp/Cntr=0.3,0.1

Type RM Length L Ch R = 1 ,12748   ,199.1,202.9,206
XS GIS Cut Line= 2
     1639066.353      585676.515     1638955.676      585832.765
#Sta/Elev= 30
       0   827.8       6  827.73      10   827.4      14  826.47      18  825.24
      20  824.97    33.9  825.17    73.8  824.33    77.8  823.73    79.8  823.06
    85.8  819.22    87.8  819.04    99.7  819.21   101.7  819.73   103.7  821.22
   107.7   825.3   111.7  828.78   121.7  837.99   127.6  842.21   129.6  843.42
   135.6   846.5   139.6  848.25   147.6  851.19   151.6  852.37   153.6  853.32
   155.6  854.46   161.6   858.9   163.6  860.18   167.5  861.93   191.5  869.46
#Mann= 3 , 0 , 0
       0      .1       0    85.8    .045       0   101.7      .1       0
Bank Sta=85.8,101.7
XS Rating Curve= 0 ,0
Exp/Cntr=0.3,0.1

Type RM Length L Ch R = 1 ,12545.1 ,218.5,215.5,212.3
XS GIS Cut Line= 2
     1638937.447      585541.098     1638820.259      585662.192
#Sta/Elev= 30
       0  827.67       4  827.43     7.9  826.99    17.8  825.38    35.7  822.68
    39.6  822.42    47.6  822.41    53.5  822.22    61.5  821.67    63.4   821.4
    65.4  820.97    67.4  819.94    69.4  817.11    71.4  814.88    79.3  814.36
    81.3  814.44    83.3  815.55    85.2  817.65    87.2  818.95    89.2  819.88
    91.2  820.54    93.2  821.02    97.1  821.77    99.1  821.99     115  822.85
   122.9  823.42   130.8  823.59   138.8  823.92   154.6  824.83   168.5  825.46
#Mann= 3 , 0 , 0
       0     .06       0    69.4    .045       0    83.3      .1       0
Bank Sta=69.4,83.3
XS Rating Curve= 0 ,0
Exp/Cntr=0.3,0.1

Type RM Length L Ch R = 1 ,12329.6 ,302.6,303.9,304.7
XS GIS Cut Line= 2
      1638777.29      585378.338     1638631.457      585577.556
#Sta/Elev= 30
       0  837.83    21.9  837.73    27.9  836.65    35.8  833.93    41.8  832.64
    43.8  831.56    55.8  823.44    61.7  820.02    63.7  819.46    79.6  819.44
    89.6   818.6    91.6  816.75    93.6  814.47    95.6  813.19    97.6  812.82
   107.5  812.72   111.5  812.89   112.7  813.23   123.4  817.45   127.4  818.58
   131.4  819.28   135.4  819.71   147.3  820.08   161.3  821.76   181.2  823.06
   185.2  823.95   195.1  826.94   199.1  827.62     229   828.8   246.9  830.15
#Mann= 3 , 0 , 0
       0     .06       0    95.6    .045       0   112.7      .1       0
Bank Sta=95.6,112.7
XS Rating Curve= 0 ,0
Exp/Cntr=0.3,0.1

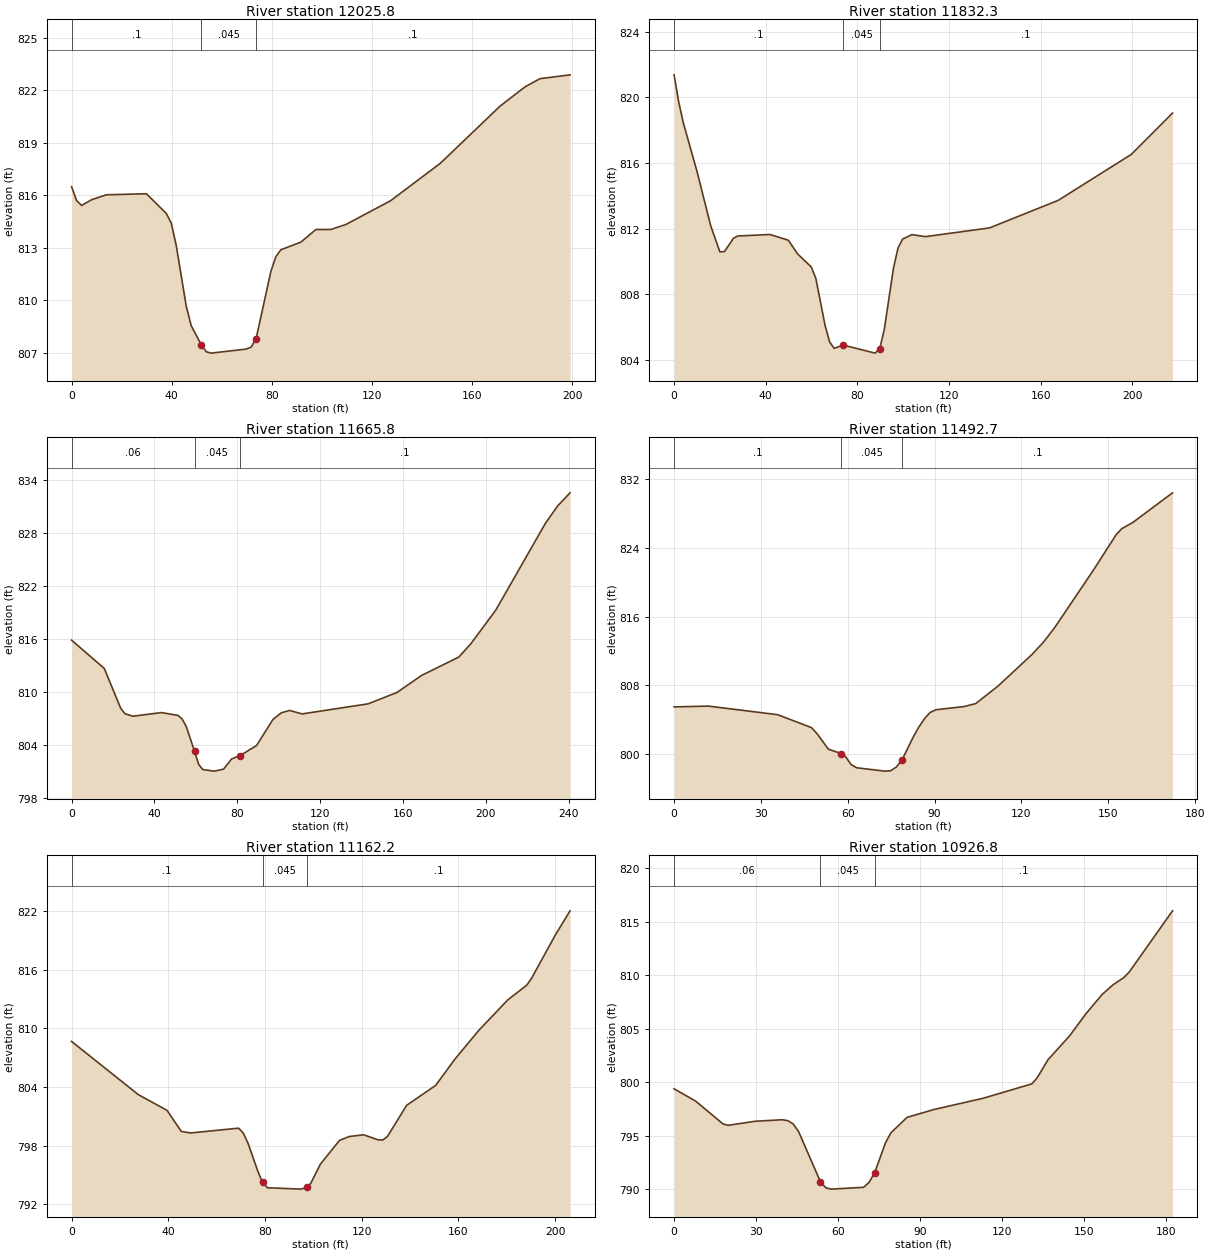
Type RM Length L Ch R = 1 ,12025.8 ,189.7,193.4,196.8
XS GIS Cut Line= 2
     1638499.947      585249.431     1638374.947      585404.379
#Sta/Elev= 30
       0  816.48       2  815.69       4  815.41       8  815.74    13.9  816.02
    29.9  816.08    37.8  814.96    39.8  814.41    41.8  813.13    45.8  809.66
    47.8  808.54    51.8  807.46    53.8  807.06    55.7  806.98    69.7  807.21
    71.7  807.32    73.7  807.81    79.6  811.64    81.6  812.49    83.6  812.88
    91.6  813.32    97.6  814.04   103.5  814.04   109.5  814.32   127.4  815.68
   147.3  817.82   171.2  821.09   181.2  822.19   187.1  822.65   199.1  822.87
#Mann= 3 , 0 , 0
       0      .1       0    51.8    .045       0    73.7      .1       0
Bank Sta=51.8,73.7
XS Rating Curve= 0 ,0
Exp/Cntr=0.3,0.1

Type RM Length L Ch R = 1 ,11832.3 ,165.5,166.5,167.6
XS GIS Cut Line= 2
     1638367.134      585127.036     1638205.676      585272.869
#Sta/Elev= 30
       0  821.37       2  819.74       4  818.46      10  815.49      16  812.17
      20  810.58      22   810.6      26  811.42    27.9  811.55    41.9  811.64
    49.9  811.29    53.9  810.46    59.9  809.66    61.9  808.96    65.9  806.11
    67.9  805.09    69.9   804.7    73.8   804.9    87.8  804.41    89.8  804.69
    91.8  805.87    95.8  809.61    97.8  810.83    99.8  811.36   103.8  811.63
   109.8  811.51   137.7  812.04   167.7  813.72   199.6  816.52   217.6  819.04
#Mann= 3 , 0 , 0
       0      .1       0    73.8    .045       0    89.8      .1       0
Bank Sta=73.8,89.8
XS Rating Curve= 0 ,0
Exp/Cntr=0.3,0.1

Type RM Length L Ch R = 1 ,11665.8 ,169.4,173.2,176.9
XS GIS Cut Line= 4
     1638251.249      585015.056     1638213.488      585043.702
     1638154.894      585091.879     1638059.842       585160.89
#Sta/Elev= 30
       0   815.9    15.8   812.7    23.7  808.21    25.7  807.59    29.6   807.3
    43.4  807.71    51.4  807.39    53.4  806.98    55.4  806.12    59.4  803.31
    61.4  801.84    63.4  801.26      69  801.09    73.4  801.32    77.3  802.47
    81.3  802.84    89.3  803.98    97.3  806.95   101.3  807.69   105.3  807.95
   111.3  807.56   143.2   808.7   157.1  809.98     169  811.91     187  813.99
   192.9  815.52   204.9  819.32   228.8  829.11   234.7  831.07   240.7  832.56
#Mann= 3 , 0 , 0
       0     .06       0    59.4    .045       0    81.3      .1       0
Bank Sta=59.4,81.3
XS Rating Curve= 0 ,0
Exp/Cntr=0.3,0.1

Type RM Length L Ch R = 1 ,11492.7 ,334.5,330.5,325.4
XS GIS Cut Line= 4
     1638126.249      584906.984     1638096.301      584926.515
     1638028.592      584965.577     1637976.509      584991.619
#Sta/Elev= 30
       0  805.47    11.9  805.56    35.8  804.56    47.5  803.05    49.4  802.35
    53.3  800.54    57.8  800.03    59.2  799.69    61.2  798.73    63.1  798.37
    72.8  797.98    74.8  798.02    76.8  798.46    78.8  799.32    82.7     802
    84.6  803.14    86.6  804.14    88.5  804.83    90.5  805.14   100.2  805.51
   104.2  805.85     112  807.92   123.6  811.57   127.5  812.97   131.4  814.67
     145  821.48   152.7  825.54   154.7  826.26   158.6     827   172.2  830.43
#Mann= 3 , 0 , 0
       0      .1       0    57.8    .045       0    78.8      .1       0
Bank Sta=57.8,78.8
XS Rating Curve= 0 ,0
Exp/Cntr=0.3,0.1

Type RM Length L Ch R = 1 ,11162.2 ,237.8,235.4,232.9
XS GIS Cut Line= 3
      1637958.28      584612.713     1637906.197      584651.775
     1637800.728      584745.525
#Sta/Elev= 30
       0  808.67    27.6  803.22    39.5   801.6    45.4  799.44    49.3  799.29
    69.1  799.78    71.1  799.25      73  798.23      77   795.4      79  794.21
      81  793.67    94.9  793.53    97.5  793.72    98.9  794.11   102.9  796.08
   110.8  798.52   114.8  798.92   120.8   799.1   126.7  798.59   128.7  798.56
   130.7  798.94   138.6  802.12   150.6  804.16   158.5  806.83   168.4  809.79
   180.4  812.92   188.3  814.44   190.3  815.15   200.2  819.62   206.2  822.06
#Mann= 3 , 0 , 0
       0      .1       0      79    .045       0    97.5      .1       0
Bank Sta=79,97.5
XS Rating Curve= 0 ,0
Exp/Cntr=0.3,0.1

Type RM Length L Ch R = 1 ,10926.8 ,222,223.9,225.8
XS GIS Cut Line= 2
     1637766.874      584452.556     1637644.478      584587.973
#Sta/Elev= 30
       0  799.39     7.9  798.24    17.9  796.11    19.8  795.98    29.8  796.36
    39.7   796.5    41.7  796.41    43.6  796.11    45.6  795.39    53.6   790.7
    55.6  790.14    57.5  790.02    69.4  790.19    71.4  790.65    73.4  791.52
    77.4  794.34    79.4  795.28    85.3  796.72    95.2  797.46   113.1   798.5
     131  799.85   132.9   800.4   136.9   802.1   144.8  804.33   150.8   806.4
   156.7  808.19   160.7   809.1   164.7  809.78   166.7  810.31   182.5  816.01
#Mann= 3 , 0 , 0
       0     .06       0    53.6    .045       0    73.4      .1       0
Bank Sta=53.6,73.4
XS Rating Curve= 0 ,0
Exp/Cntr=0.3,0.1

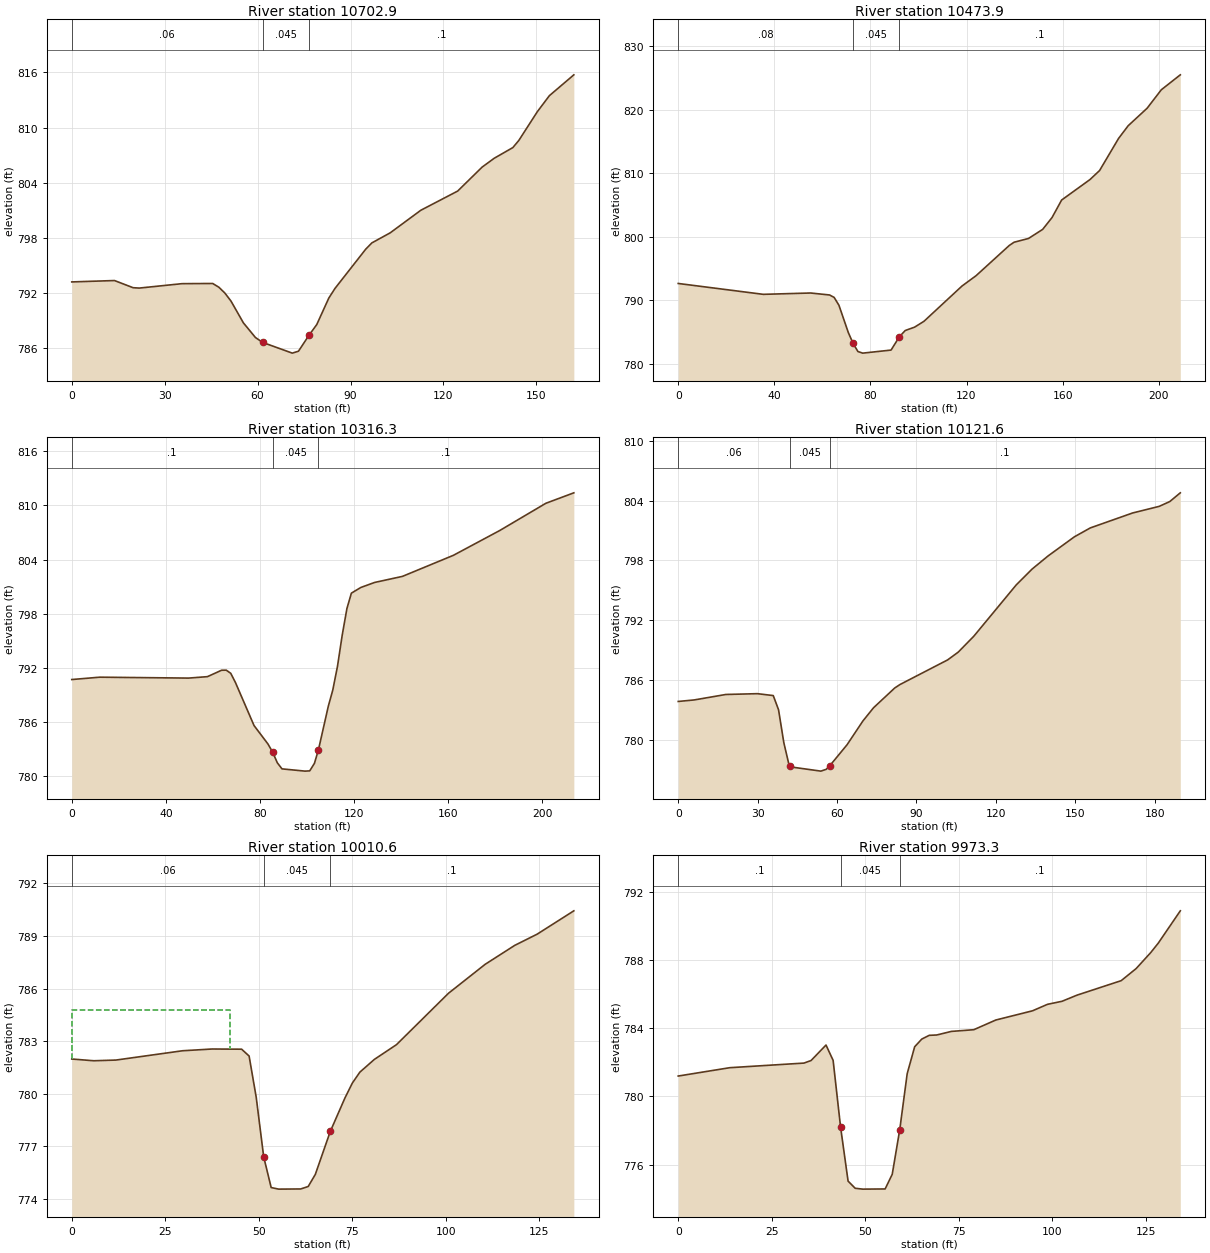
Type RM Length L Ch R = 1 ,10702.9 ,228,229,229.6
XS GIS Cut Line= 2
     1637615.832      584295.004     1637497.342      584405.681
#Sta/Elev= 30
       0   793.2    13.8  793.35    19.8  792.57    21.8  792.53    35.6  793.01
    45.5  793.03    47.5  792.62    49.4     792    51.4  791.12    55.4  788.75
    59.3  787.15    61.6  786.62    71.2  785.45    73.2  785.66    76.6   787.4
    79.1  788.56      83  791.45      85   792.5    94.9  796.76    96.9  797.45
   102.8  798.54   112.7     801   124.6  803.09   132.5   805.7   136.4  806.66
   142.4  807.82   144.3  808.58   150.3  811.72   154.2  813.47   162.1  815.74
#Mann= 3 , 0 , 0
       0     .06       0    61.6    .045       0    76.6      .1       0
Bank Sta=61.6,76.6
XS Rating Curve= 0 ,0
Exp/Cntr=0.3,0.1

Type RM Length L Ch R = 1 ,10473.9 ,151.5,157.7,162.7
XS GIS Cut Line= 3
     1637468.697      584123.129     1637380.155      584201.254
     1637335.884      584280.681
#Sta/Elev= 30
       0  792.67    35.4  790.96    55.1  791.17      63  790.86    64.9  790.48
    66.9  789.24    70.8  784.95    72.8  783.23    74.8  781.96    76.8  781.71
    88.6  782.19    92.1  784.31    94.5  785.27    98.4   785.8   102.3  786.72
   118.1  792.26     124   793.9   137.8  798.65   139.8  799.16   145.8  799.75
   151.7  801.18   155.6  803.04   159.6   805.8   171.4  809.02   175.4  810.44
   183.3  815.49   187.3  817.49   195.2  820.25   201.1  823.15     209   825.5
#Mann= 3 , 0 , 0
       0     .08       0    72.8    .045       0    92.1      .1       0
Bank Sta=72.8,92.1
XS Rating Curve= 0 ,0
Exp/Cntr=0.3,0.1

Type RM Length L Ch R = 1 ,10316.3 ,197.8,194.6,190.6
XS GIS Cut Line= 4
     1637365.832        584042.4      1637302.03      584074.952
     1637256.457       584098.39     1637227.811      584184.327
#Sta/Elev= 30
       0  790.69    11.9  790.95    49.7  790.85    57.7  791.01    63.7  791.72
    65.7  791.73    67.6  791.38    69.6  790.36    77.5  785.59    83.4  783.55
    85.4  782.65    87.4  781.46    89.4  780.78    99.2  780.53   101.2  780.56
   103.2   781.4   104.9   782.9   109.1  787.74     111  789.53     113  792.17
     115  795.61     117  798.56   118.9  800.27   122.9   800.9   128.8  801.46
   140.6  802.13   162.3  804.47     182  807.22   201.6  810.24   213.5   811.4
#Mann= 3 , 0 , 0
       0      .1       0    85.4    .045       0   104.9      .1       0
Bank Sta=85.4,104.9
XS Rating Curve= 0 ,0
Exp/Cntr=0.3,0.1

Type RM Length L Ch R = 1 ,10121.6 ,123.9,111,98
XS GIS Cut Line= 3
     1637283.801      583874.431     1637203.072      583933.025
      1637152.29      584007.244
#Sta/Elev= 30
       0  783.85       6     784      18  784.55    29.9  784.63    35.9  784.44
    37.9  783.02    39.9  779.71    41.9  777.44    42.2  777.41    43.9  777.23
    53.9  776.86    55.9  777.04    57.2  777.38    63.8  779.51    69.8   781.9
    73.8  783.22    81.8   785.2    83.8  785.55   101.8  788.02   105.8   788.8
   111.7   790.4   127.7  795.54   133.7  797.13   139.7  798.44   149.7  800.37
   155.7  801.26   171.7  802.76   181.7  803.42   185.7   803.9   189.7  804.78
#Mann= 3 , 0 , 0
       0     .06       0    42.2    .045       0    57.2      .1       0
Bank Sta=42.2,57.2
XS Rating Curve= 0 ,0
Exp/Cntr=0.3,0.1

Type RM Length L Ch R = 1 ,10010.6 ,37,37.3,37
XS GIS Cut Line= 2
     1637206.978      583753.338     1637154.894      583877.036
#Sta/Elev= 25
       0  781.98     5.9  781.88    11.8  781.92    29.6  782.45    37.5  782.55
    45.4  782.54    47.4  782.15    49.3   779.8    51.3   776.4    53.3  774.65
    55.3  774.56    61.2  774.57    63.2  774.71    65.1   775.4    69.1  777.85
      73  779.75      75  780.61      77  781.23    80.9  781.96    86.8   782.8
   100.7  785.73   110.5  787.38   118.4  788.46   124.4   789.1   134.2  790.43
#Mann= 3 , 0 , 0
       0     .06       0    51.3    .045       0    69.1      .1       0
#XS Ineff= 2 , 0
           42.16  784.77
Permanent Ineff=
       F       F
Bank Sta=51.3,69.1
XS Rating Curve= 0 ,0
Exp/Cntr=0.3,0.1

Type RM Length L Ch R = 1 ,9973.3  ,79.5,81.1,83.2
XS GIS Cut Line= 2
     1637179.634      583732.504     1637127.551      583856.202
#Sta/Elev= 30
       0   781.2    13.8  781.69    33.6  781.96    35.5  782.11    39.5  783.02
    41.4  782.12    43.4  778.19    45.4  775.03    47.3  774.61    49.3  774.56
    55.3  774.57    57.2  775.43    59.2  778.04    61.2  781.34    63.2  782.92
    65.1  783.37    67.1  783.59    69.1  783.61      73  783.82      79  783.92
    84.9  784.49    94.7  785.03    98.7  785.41   102.6  785.59   106.6  785.95
   118.4   786.8   122.4  787.51   126.3  788.45   128.3     789   134.2   790.9
#Mann= 3 , 0 , 0
       0      .1       0    43.4    .045       0    59.2      .1       0
Bank Sta=43.4,59.2
XS Rating Curve= 0 ,0
Exp/Cntr=0.3,0.1

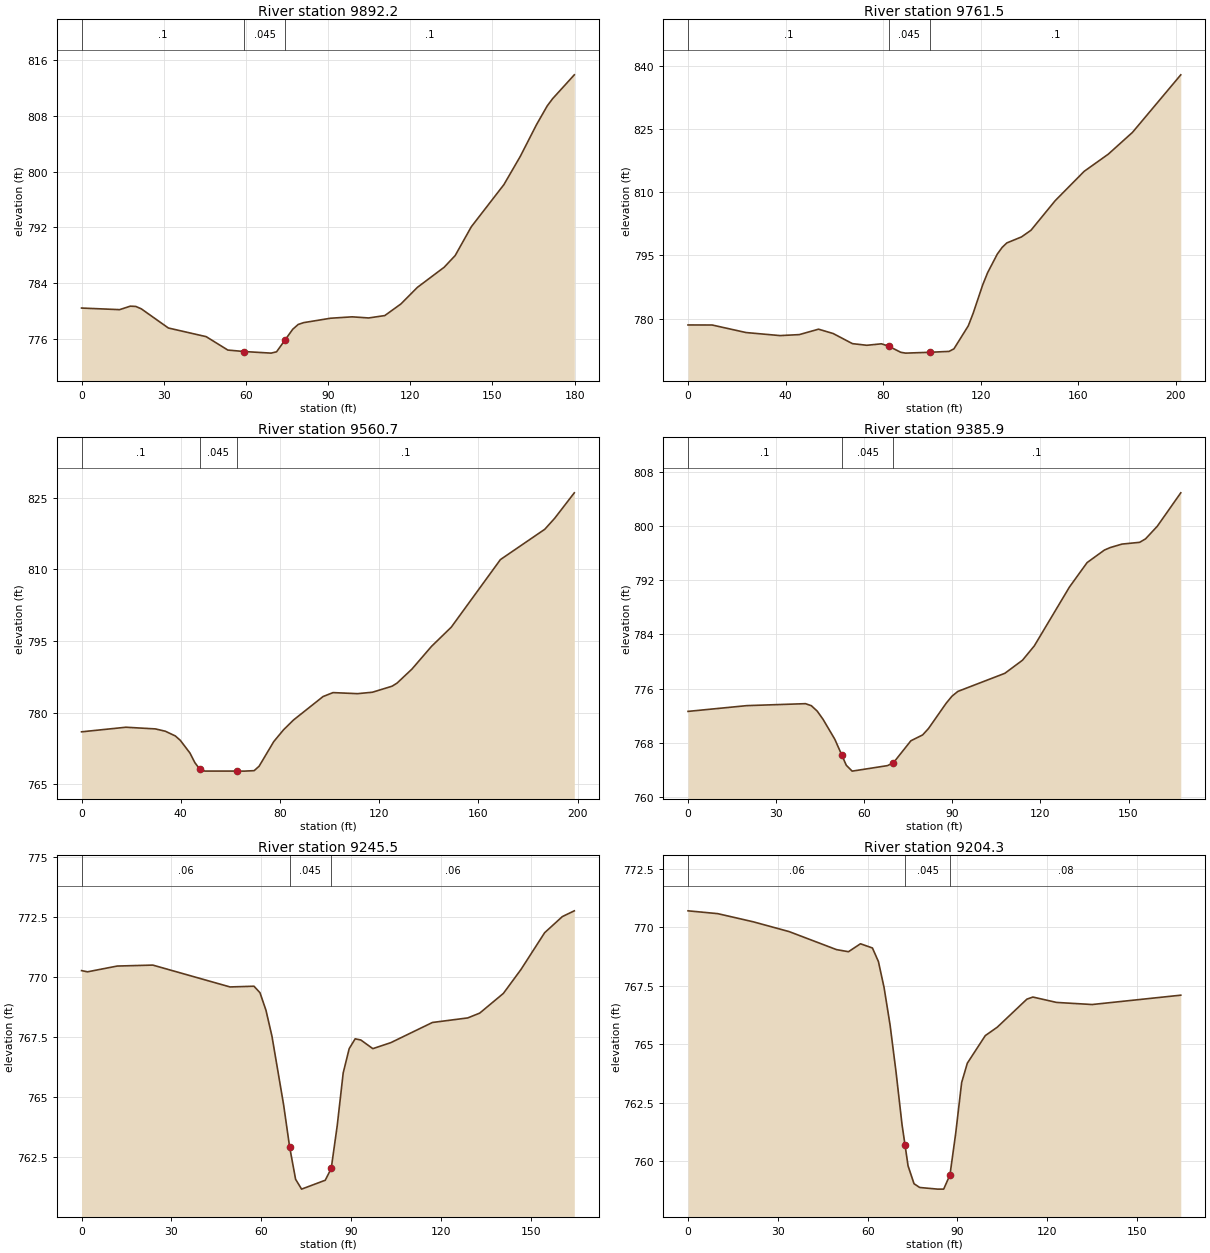
Type RM Length L Ch R = 1 ,9892.2  ,120.1,130.8,141
XS GIS Cut Line= 4
     1637128.853      583681.723     1637110.624      583699.952
     1637075.467      583772.869     1637018.176      583818.442
#Sta/Elev= 30
       0  780.45    13.9  780.22    17.8  780.72    19.8  780.68    21.8  780.34
    31.7  777.59    45.5  776.35    53.4  774.43    59.3  774.22    69.2  773.99
    71.2  774.18    74.3  775.88    77.1  777.41    79.1   778.1    81.1  778.36
    90.9  778.99    98.8  779.19   104.8  779.03   110.7  779.37   116.6  781.04
   122.6  783.41   132.4   786.3   136.4  787.97   142.3   792.1   154.2  798.14
   160.2   802.2   166.1  806.73     170  809.41     172  810.46   179.9  813.87
#Mann= 3 , 0 , 0
       0      .1       0    59.3    .045       0    74.3      .1       0
Bank Sta=59.3,74.3
XS Rating Curve= 0 ,0
Exp/Cntr=0.3,0.1

Type RM Length L Ch R = 1 ,9761.5  ,199.9,200.8,201.4
XS GIS Cut Line= 3
     1637055.936      583594.484      1637020.78      583634.848
     1636903.592      583725.994
#Sta/Elev= 30
       0  778.52     9.9  778.51    23.8  776.72    37.7     776    45.6  776.23
    53.5  777.52    59.5  776.49    67.4  774.09    73.3   773.7    79.3  774.05
    82.2   773.5    87.2  772.04    89.2  771.84    99.1  772.04     107  772.25
     109  772.85   114.9  778.32   116.9  781.31   120.8  788.03   122.8   790.9
   126.8  795.35   128.8  796.93   130.7  797.98   136.7   799.4   140.6  800.99
   150.5  807.99   162.4  814.96   172.3  819.04   182.2   824.2     202  837.85
#Mann= 3 , 0 , 0
       0      .1       0    82.2    .045       0    99.1      .1       0
Bank Sta=82.2,99.1
XS Rating Curve= 0 ,0
Exp/Cntr=0.3,0.1

Type RM Length L Ch R = 1 ,9560.7  ,177.3,174.8,172.3
XS GIS Cut Line= 2
     1636953.072      583447.348     1636791.613      583563.234
#Sta/Elev= 30
       0  775.97    17.9  776.93    29.8  776.58    33.8  776.09    37.8  775.11
    39.8   774.2    43.7  771.54    45.7  769.51    47.6   768.2    49.7  767.75
    62.6  767.75    65.6  767.74    69.6  767.84    71.6  768.77    77.5  773.92
    81.5  776.42    85.5  778.46    97.4  783.36   101.4  784.18   111.3  783.96
   117.3  784.26   125.2  785.52   127.2  786.16   133.2  789.09   141.1  793.85
   149.1  797.89   168.9  812.03   186.8  818.38   190.8  820.69   198.7  826.01
#Mann= 3 , 0 , 0
       0      .1       0    47.6    .045       0    62.6      .1       0
Bank Sta=47.6,62.6
XS Rating Curve= 0 ,0
Exp/Cntr=0.3,0.1

Type RM Length L Ch R = 1 ,9385.9  ,117.3,140.4,162.6
XS GIS Cut Line= 2
     1636843.697      583304.119     1636718.697      583416.098
#Sta/Elev= 30
       0  772.65      20   773.5      40  773.79      42  773.49      44  772.69
      46  771.47      50  768.53    52.4  766.18    53.9   764.7    55.9  763.84
    67.9  764.65    69.9  765.05    75.9  768.32    79.9  769.18    81.9  770.13
    87.9  773.85    89.9   774.9    91.9   775.6   107.9  778.27   113.9   780.2
   117.9   782.3   129.9     791   135.9   794.6   141.8  796.45   143.8  796.82
   147.8  797.33   153.8  797.59   155.8   798.1   159.8  799.96   167.8  804.89
#Mann= 3 , 0 , 0
       0      .1       0    52.4    .045       0    69.9      .1       0
Bank Sta=52.4,69.9
XS Rating Curve= 0 ,0
Exp/Cntr=0.3,0.1

Type RM Length L Ch R = 1 ,9245.5  ,41.2,41.2,42.5
XS GIS Cut Line= 3
     1636820.259      583239.015     1636706.978      583209.067
     1636669.217      583180.421
#Sta/Elev= 30
       0  770.27       2  770.22    11.9  770.46    23.8   770.5    49.6  769.59
    57.6  769.62    59.6  769.35    61.6  768.62    63.6  767.54    67.5  764.68
    69.5  762.93    71.5  761.58    73.5  761.17    81.4  761.54    83.4  762.03
    85.4  763.81    87.4  766.01    89.4  767.02    91.4  767.43    93.3  767.38
    97.3  767.02   103.3  767.27   117.2  768.11     129   768.3     133   768.5
   140.9  769.32   146.8  770.32   154.7  771.85   160.6  772.52   164.6  772.76
#Mann= 3 , 0 , 0
       0     .06       0    69.5    .045       0    83.4     .06       0
Bank Sta=69.5,83.4
XS Rating Curve= 0 ,0
Exp/Cntr=0.3,0.1

Type RM Length L Ch R = 1 ,9204.3  ,132.5,106.8,79.8
XS GIS Cut Line= 3
     1636828.072      583199.952      1636714.79      583170.004
      1636677.03      583141.359
#Sta/Elev= 30
       0  770.71     9.9  770.59    21.8  770.24    33.8  769.82    49.6  769.05
    53.6  768.96    57.6   769.3    61.6  769.12    63.6  768.54    65.5  767.42
    67.5  765.82    69.5   763.8    71.5  761.55    72.5  760.68    73.5   759.8
    75.5  759.03    77.4  758.87    83.4   758.8    85.4   758.8    87.5  759.41
    89.4  761.17    91.4  763.36    93.3  764.19    99.3  765.37   103.3  765.73
   113.2  766.93   115.2  767.02   123.1  766.79     135   766.7   164.6   767.1
#Mann= 3 , 0 , 0
       0     .06       0    72.5    .045       0    87.5     .08       0
Bank Sta=72.5,87.5
XS Rating Curve= 0 ,0
Exp/Cntr=0.3,0.1

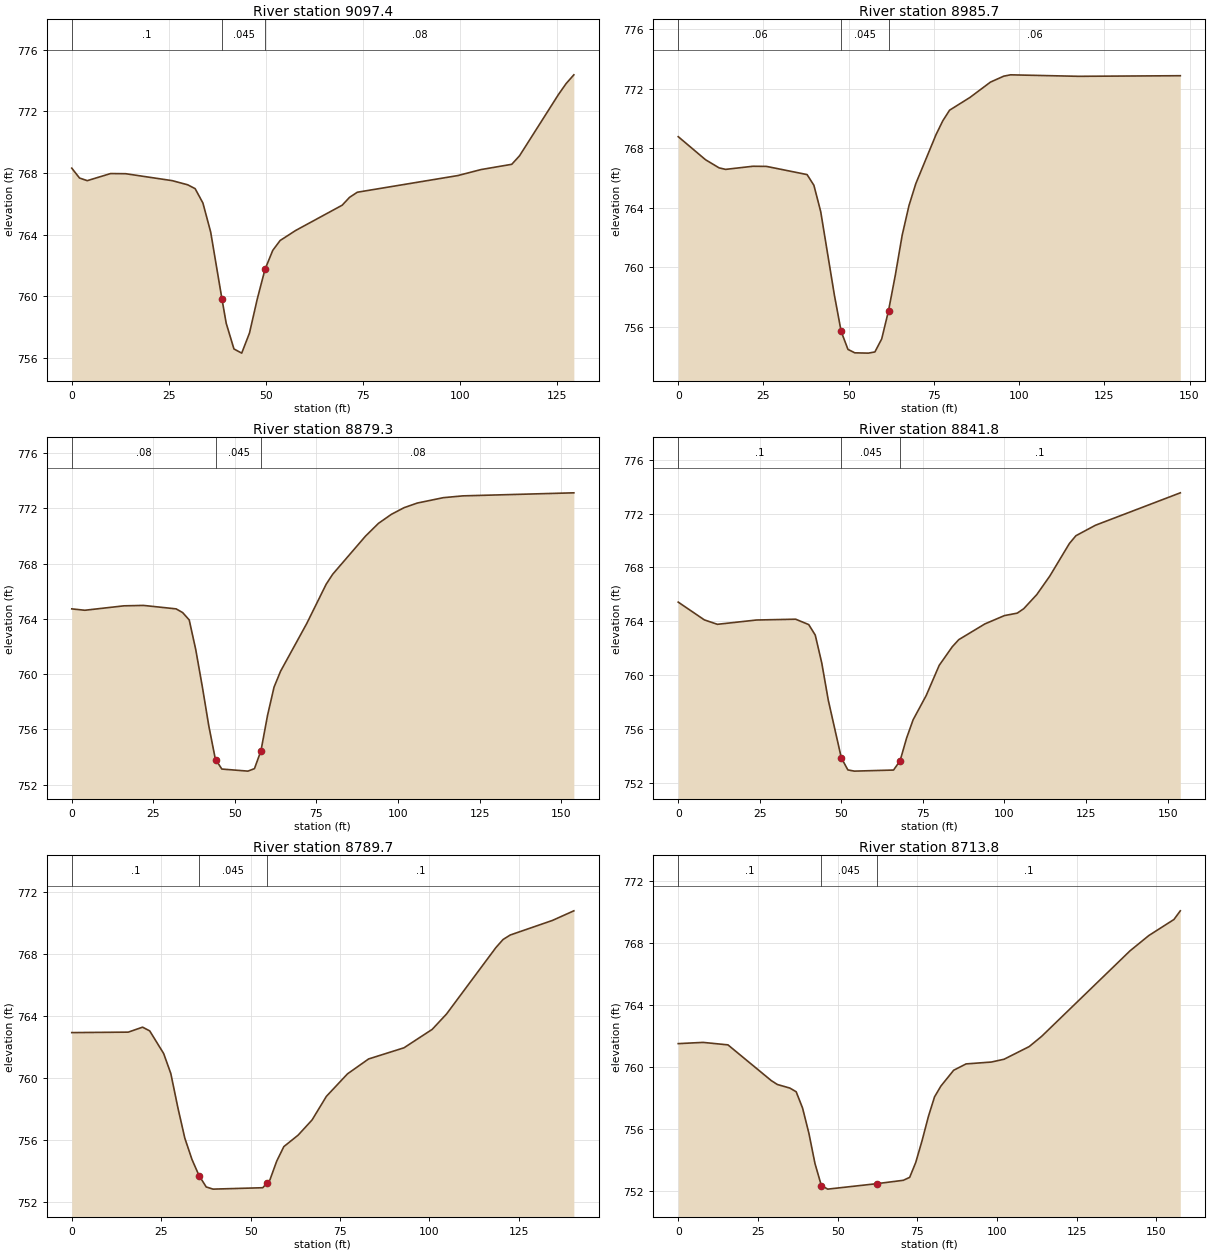
Type RM Length L Ch R = 1 ,9097.4  ,111.9,111.7,110.6
XS GIS Cut Line= 2
     1636718.697      583059.327     1636635.363      583158.286
#Sta/Elev= 30
       0  768.31       2  767.67       4   767.5      10  767.96    13.9  767.95
    25.9   767.5    29.9  767.23    31.8  766.98    33.8  766.05    35.8  764.17
    38.7  759.84    39.8  758.26    41.8  756.59    43.8  756.32    45.8  757.62
    47.8  759.82    49.8  761.75    51.8  762.98    53.7  763.62    57.7  764.27
    69.7  765.91    71.6  766.42    73.6  766.75    99.5  767.83   105.5  768.22
   113.4  768.56   115.4  769.11   125.4  773.07   127.4  773.79   129.4  774.36
#Mann= 3 , 0 , 0
       0      .1       0    38.7    .045       0    49.8     .08       0
Bank Sta=38.7,49.8
XS Rating Curve= 0 ,0
Exp/Cntr=0.3,0.1

Type RM Length L Ch R = 1 ,8985.7  ,110.1,106.4,102.9
XS GIS Cut Line= 3
     1636640.572        582979.9     1636615.832      583008.546
     1636548.124      583094.484
#Sta/Elev= 30
       0  768.78       8  767.23      12  766.68    13.9  766.58    21.9  766.79
    25.9  766.78    37.8  766.23    39.8  765.51    41.8  763.74    45.8  758.14
    47.8  755.68    49.8  754.47    51.8  754.24    55.8  754.22    57.7   754.3
    59.7  755.18    61.7  757.08    63.7  759.48    65.7  762.15    67.7  764.15
    69.7  765.62    75.6   768.9    77.6  769.84    79.6  770.56    85.6  771.42
    91.6  772.45    95.5  772.85    97.5  772.94   117.4  772.84   147.3  772.88
#Mann= 3 , 0 , 0
       0     .06       0    47.8    .045       0    61.7     .06       0
Bank Sta=47.8,61.7
XS Rating Curve= 0 ,0
Exp/Cntr=0.3,0.1

Type RM Length L Ch R = 1 ,8879.3  ,37.5,37.5,37.5
XS GIS Cut Line= 2
     1636544.217      582914.796     1636468.697      583048.911
#Sta/Elev= 30
       0  764.72       4  764.62      16  764.94      22  764.97      32  764.72
      34  764.45      36  763.92      38  761.78      40  759.12      42  756.27
      44  753.87    44.2   753.8      46  753.14      54  752.99      56  753.17
      58  754.47      60  757.01      62  759.06      64  760.21      72  763.65
      78  766.51      80  767.23      90  769.97      94   770.9      98  771.56
   101.9  772.04   105.9  772.37   113.9  772.76   119.9  772.89   153.9  773.11
#Mann= 3 , 0 , 0
       0     .08       0    44.2    .045       0      58     .08       0
Bank Sta=44.2,58
XS Rating Curve= 0 ,0
Exp/Cntr=0.3,0.1

Type RM Length L Ch R = 1 ,8841.8  ,47.8,52.2,56.6
XS GIS Cut Line= 2
     1636518.176      582884.848     1636442.655      583018.963
#Sta/Elev= 30
       0  765.42       8   764.1      12  763.77      24  764.09      36  764.15
      40  763.75      42  762.97      44  760.89      46  758.12      50  753.83
      52  752.94      54  752.85      66  752.93      68  753.62      70  755.31
      72  756.67      76  758.47      80  760.72      84   762.1      86  762.63
      94   763.8     100  764.42   103.9   764.6   105.9  764.93   109.9  765.98
   113.9  767.36   119.9  769.78   121.9  770.36   127.9  771.14   153.9  773.55
#Mann= 3 , 0 , 0
       0      .1       0      50    .045       0      68      .1       0
Bank Sta=50,68
XS Rating Curve= 0 ,0
Exp/Cntr=0.3,0.1

Type RM Length L Ch R = 1 ,8789.7  ,76.2,75.9,74.8
XS GIS Cut Line= 2
     1636473.905      582875.734     1636382.759      582982.504
#Sta/Elev= 30
       0  762.93    15.8  762.96    19.8  763.28    21.8  763.04    25.7  761.58
    27.7  760.29    29.7  758.06    31.6  756.14    33.6  754.76    35.6  753.71
    37.6  752.98    39.5  752.84    53.4  752.93    54.6  753.23    55.4  753.43
    57.3  754.64    59.3  755.58    63.3  756.32    67.2   757.3    71.2  758.82
    77.1  760.27      83  761.23    92.9  761.95   100.8  763.14   104.8  764.13
   118.6  768.41   120.6  768.93   122.6  769.22   134.4  770.16   140.4  770.78
#Mann= 3 , 0 , 0
       0      .1       0    35.6    .045       0    54.6      .1       0
Bank Sta=35.6,54.6
XS Rating Curve= 0 ,0
Exp/Cntr=0.3,0.1

Type RM Length L Ch R = 1 ,8713.8  ,53.8,57.7,61.9
XS GIS Cut Line= 3
     1636417.915      582831.463     1636391.874        582854.9
     1636316.353      582951.254
#Sta/Elev= 30
       0  761.51     7.8  761.59    15.6  761.43    29.2  759.12    31.1  758.87
      35  758.64      37   758.4      39  757.35      41  755.71    42.9  753.76
    44.9  752.34    46.9  752.11    62.2  752.46    70.6  752.68    72.6  752.87
    74.5  753.83    76.5  755.25    78.5  756.82    80.4  758.07    82.4  758.77
    86.4  759.79    90.3   760.2    98.2  760.32   102.2   760.5   110.1  761.32
     114  761.98   141.7   767.5   147.6  768.49   155.5  769.53   157.5  770.09
#Mann= 3 , 0 , 0
       0      .1       0    44.9    .045       0    62.2      .1       0
Bank Sta=44.9,62.2
XS Rating Curve= 0 ,0
Exp/Cntr=0.3,0.1