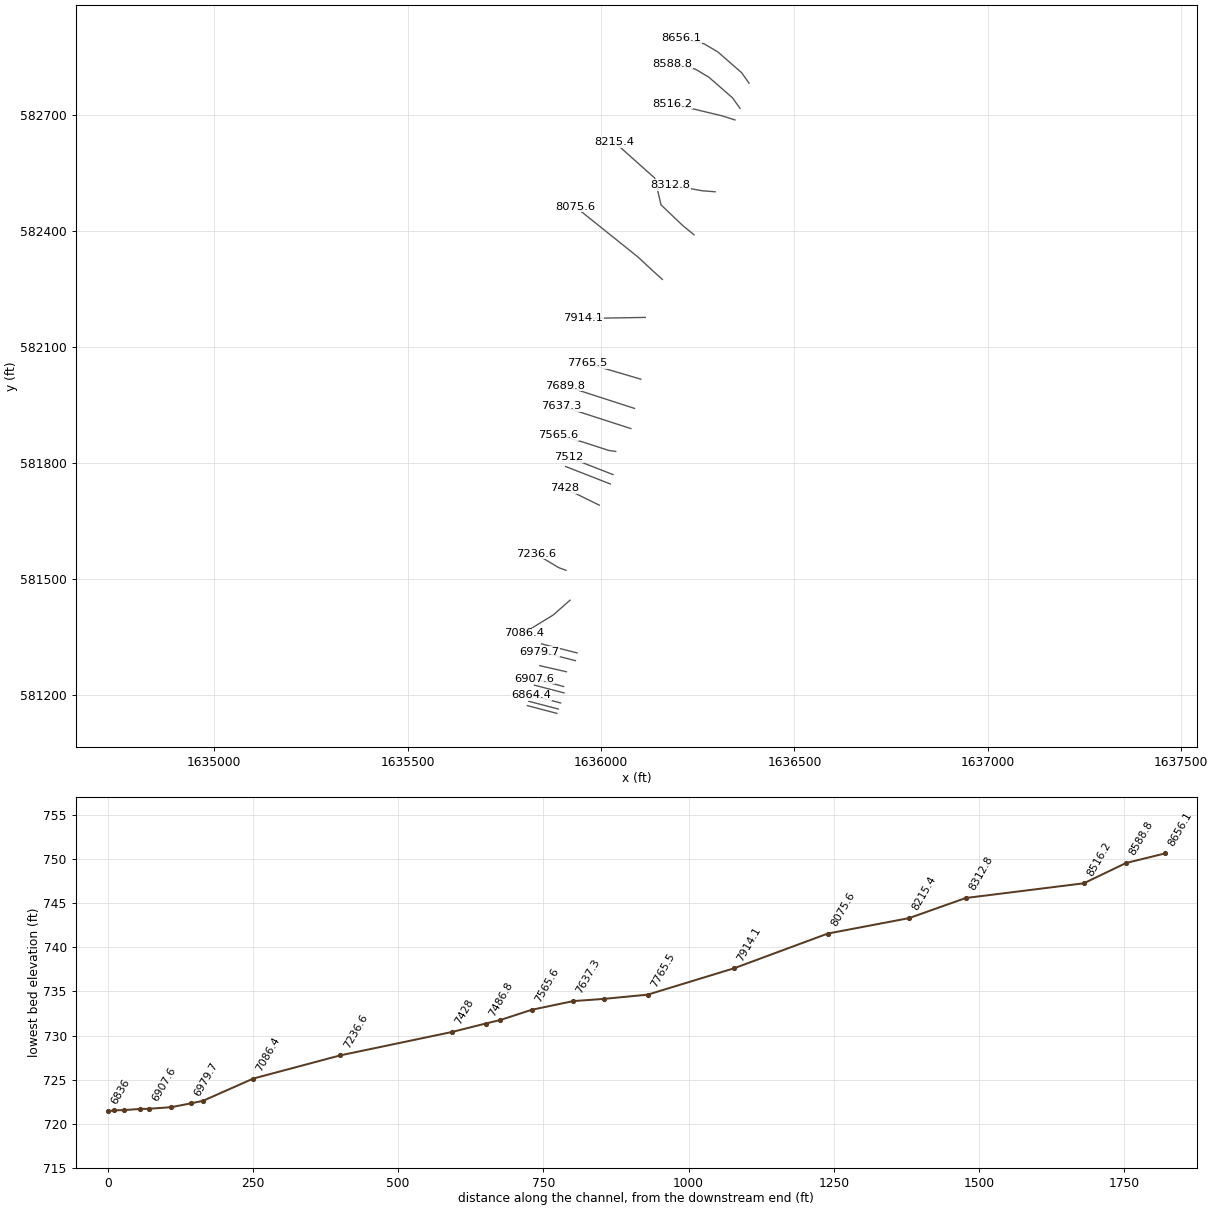
HEC-RAS study LONGRUN.prj: LONGRUN

--- LONGRUN.g01 (geometry) --- (continued)

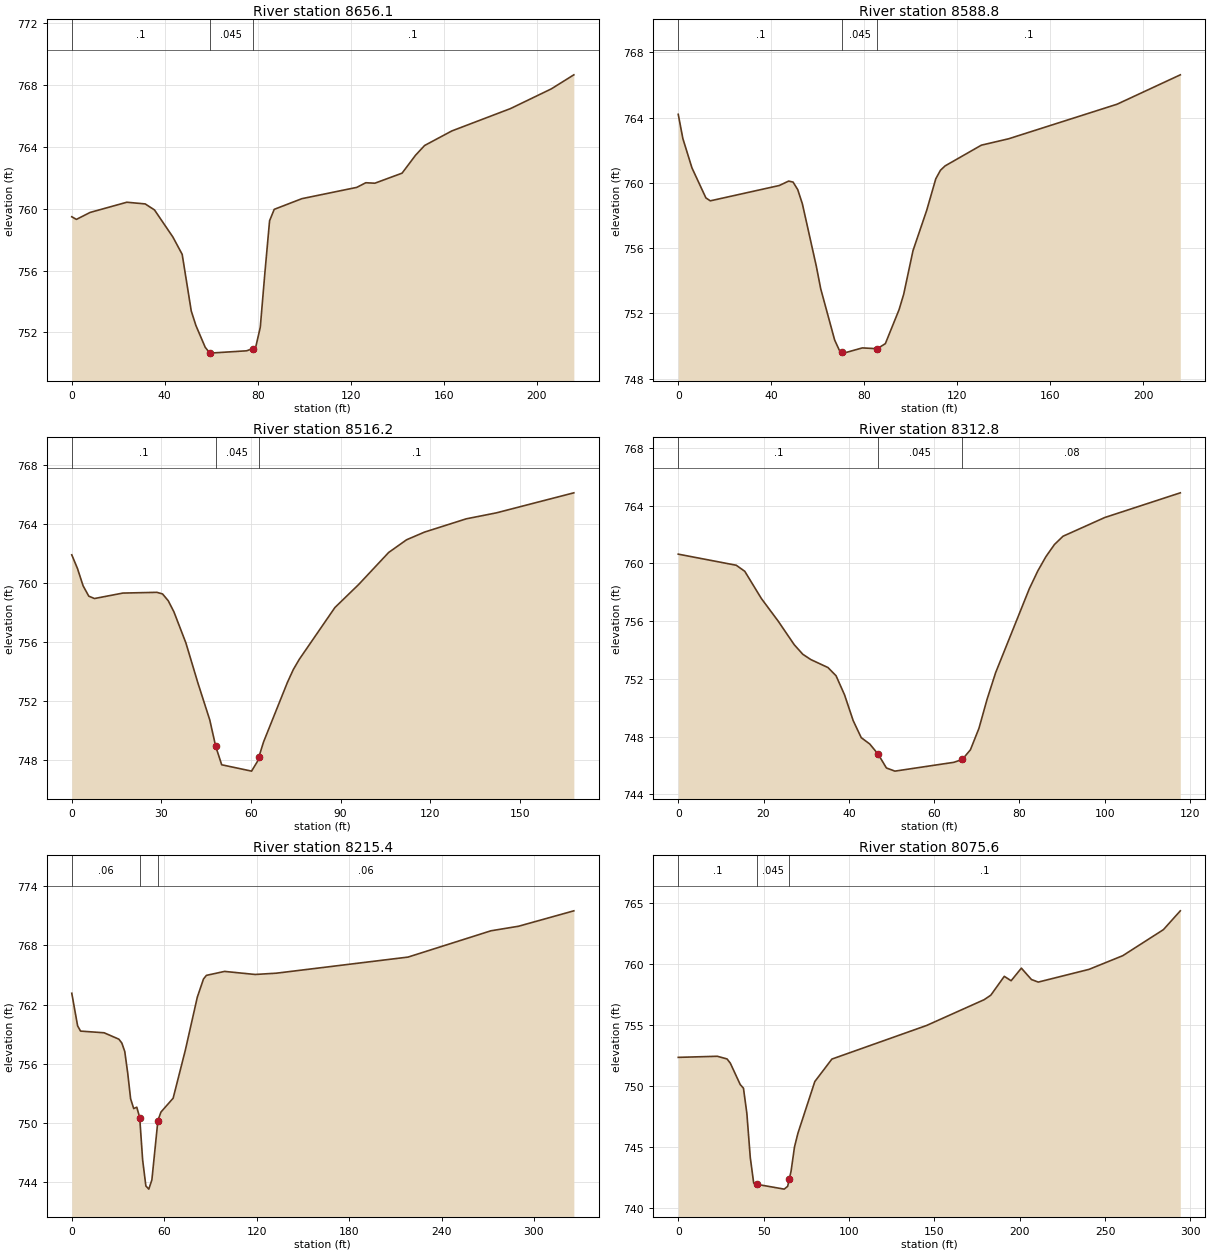
Type RM Length L Ch R = 1 ,8656.1  ,68.1,67.3,66.8
XS GIS Cut Line= 5
     1636382.759      582781.984     1636363.228      582809.327
      1636302.03      582862.713     1636266.874      582883.546
      1636208.28      582897.869
#Sta/Elev= 30
       0  759.48       2  759.31     7.9  759.76    23.7  760.42    31.6  760.31
    35.6  759.92    43.5  758.17    47.5  757.05    51.4  753.39    53.4  752.45
    57.4  751.04    59.4  750.66    75.2  750.81    77.8  750.95    79.2  751.09
    81.1  752.33    83.1  755.88    85.1  759.22    87.1  759.96      99  760.65
   122.6  761.38   126.5  761.68   130.4  761.65   142.1   762.3   147.9  763.46
   151.8  764.09   163.5  765.03   188.8  766.48   206.3  767.75     216  768.66
#Mann= 3 , 0 , 0
       0      .1       0    59.4    .045       0    77.8      .1       0
Bank Sta=59.4,77.8
XS Rating Curve= 0 ,0
Exp/Cntr=0.3,0.1

Type RM Length L Ch R = 1 ,8588.8  ,60.7,72.7,83.9
XS GIS Cut Line= 5
     1636359.322      582716.879      1636339.79      582744.223
     1636278.592      582797.609     1636243.436      582818.442
     1636184.842      582832.765
#Sta/Elev= 30
       0   764.2       2  762.71     5.9  760.92    11.9  759.08    13.8   758.9
    43.5  759.84    47.5  760.11    49.4  760.05    51.4  759.59    53.4  758.72
    59.4   754.9    61.3  753.51    67.3  750.37    69.3  749.75    70.6  749.63
    71.2  749.57    79.2  749.89    85.6  749.84    89.1  750.15      95  752.23
      97  753.18     101  755.85   106.9  758.32   110.8  760.25   112.8  760.77
   114.8  761.04   130.4  762.31   142.1   762.7   188.8  764.82     216  766.62
#Mann= 3 , 0 , 0
       0      .1       0    70.6    .045       0    85.6      .1       0
Bank Sta=70.6,85.6
XS Rating Curve= 0 ,0
Exp/Cntr=0.3,0.1

Type RM Length L Ch R = 1 ,8516.2  ,201.9,203.3,204.7
XS GIS Cut Line= 3
     1636346.301      582686.931     1636313.749      582697.348
      1636183.54      582728.598
#Sta/Elev= 30
       0  761.92     1.9     761     3.8  759.82     5.7  759.12     7.6  758.96
    17.1  759.33    28.5  759.38    30.4  759.27    32.3  758.81    34.2  758.06
    38.2  755.96    42.2  753.26    46.2  750.74    48.2  748.94    50.2   747.7
    60.2  747.27    62.2  747.94    62.6   748.2    64.2  749.24    72.2  753.28
    74.2  754.16    76.2  754.85    88.1  758.35    96.1  759.92   106.1  762.08
   112.1  762.94   118.1  763.46   132.1  764.36   142.1  764.76   168.1  766.12
#Mann= 3 , 0 , 0
       0      .1       0    48.2    .045       0    62.6      .1       0
Bank Sta=48.2,62.6
XS Rating Curve= 0 ,0
Exp/Cntr=0.3,0.1

Type RM Length L Ch R = 1 ,8312.8  ,110.4,97.5,83.6
XS GIS Cut Line= 3
     1636294.999      582501.254     1636262.013      582503.859
     1636178.679      582518.616
#Sta/Elev= 30
       0  760.64    13.6  759.87    15.6  759.45    19.5  757.56    23.4  756.01
    27.2  754.36    29.2   753.7    31.1  753.33    35.1  752.78      37  752.21
      39  750.88      41  749.11    42.9  747.92    44.9  747.48    46.9  746.76
    48.8  745.82    50.8   745.6    64.6  746.21    66.6  746.41    68.5  747.08
    70.5  748.57    72.4  750.58    74.4  752.42    82.3  758.24    84.3  759.48
    86.2  760.47    88.2  761.31    90.2  761.88     100  763.18   117.7  764.89
#Mann= 3 , 0 , 0
       0      .1       0    46.9    .045       0    66.6     .08       0
Bank Sta=46.9,66.6
XS Rating Curve= 0 ,0
Exp/Cntr=0.3,0.1

Type RM Length L Ch R = 1 ,8215.4  ,139.9,139.8,139.9
XS GIS Cut Line= 5
     1636240.311      582390.143     1636210.797      582414.449
     1636155.242        582467.4     1636138.749      582536.845
     1636034.582      582629.727
#Sta/Elev= 30
       0  763.14     3.8  759.84     5.7  759.31      21  759.14    30.6  758.49
    32.5   758.1    34.4  757.25    36.3  755.08    38.2  752.46    40.2  751.47
    42.2  751.61    44.1  750.56      46  746.28    48.1  743.64      50  743.32
      52  744.25    55.9  750.25    57.9  751.12    65.8  752.52    73.7  757.37
    81.5  762.75    85.5  764.58    87.4  764.95    99.2  765.35     119  765.04
   132.8  765.17   218.3   766.8   272.1  769.46     290  769.92   325.9  771.48
#Mann= 3 , 0 , 0
       0     .06       0    44.1    .045       0    55.9     .06       0
Bank Sta=44.1,55.9
XS Rating Curve= 0 ,0
Exp/Cntr=0.3,0.1

Type RM Length L Ch R = 1 ,8075.6  ,144,161.5,178.6
XS GIS Cut Line= 4
     1636158.714      582274.692     1636131.804      582298.997
     1636095.346      582332.852     1635933.019       582463.06
#Sta/Elev= 30
       0  752.35    22.9  752.44    28.6  752.22    30.5  751.88    36.3  750.13
    38.2  749.83    40.2  747.77    42.2  744.16    44.2  742.07    46.2  741.96
    62.1  741.57    64.1   741.8    65.1  742.42    66.1  743.04    68.1  745.02
    70.1  746.14      80  750.37      90  752.21   145.5  754.96   179.2  757.07
   183.1  757.44     191  758.98     195  758.62     201  759.65   206.9  758.72
   210.9  758.51   240.6  759.55   260.4  760.67   284.2   762.8   294.1  764.34
#Mann= 3 , 0 , 0
       0      .1       0    46.2    .045       0    65.1      .1       0
Bank Sta=46.2,65.1
XS Rating Curve= 0 ,0
Exp/Cntr=0.3,0.1

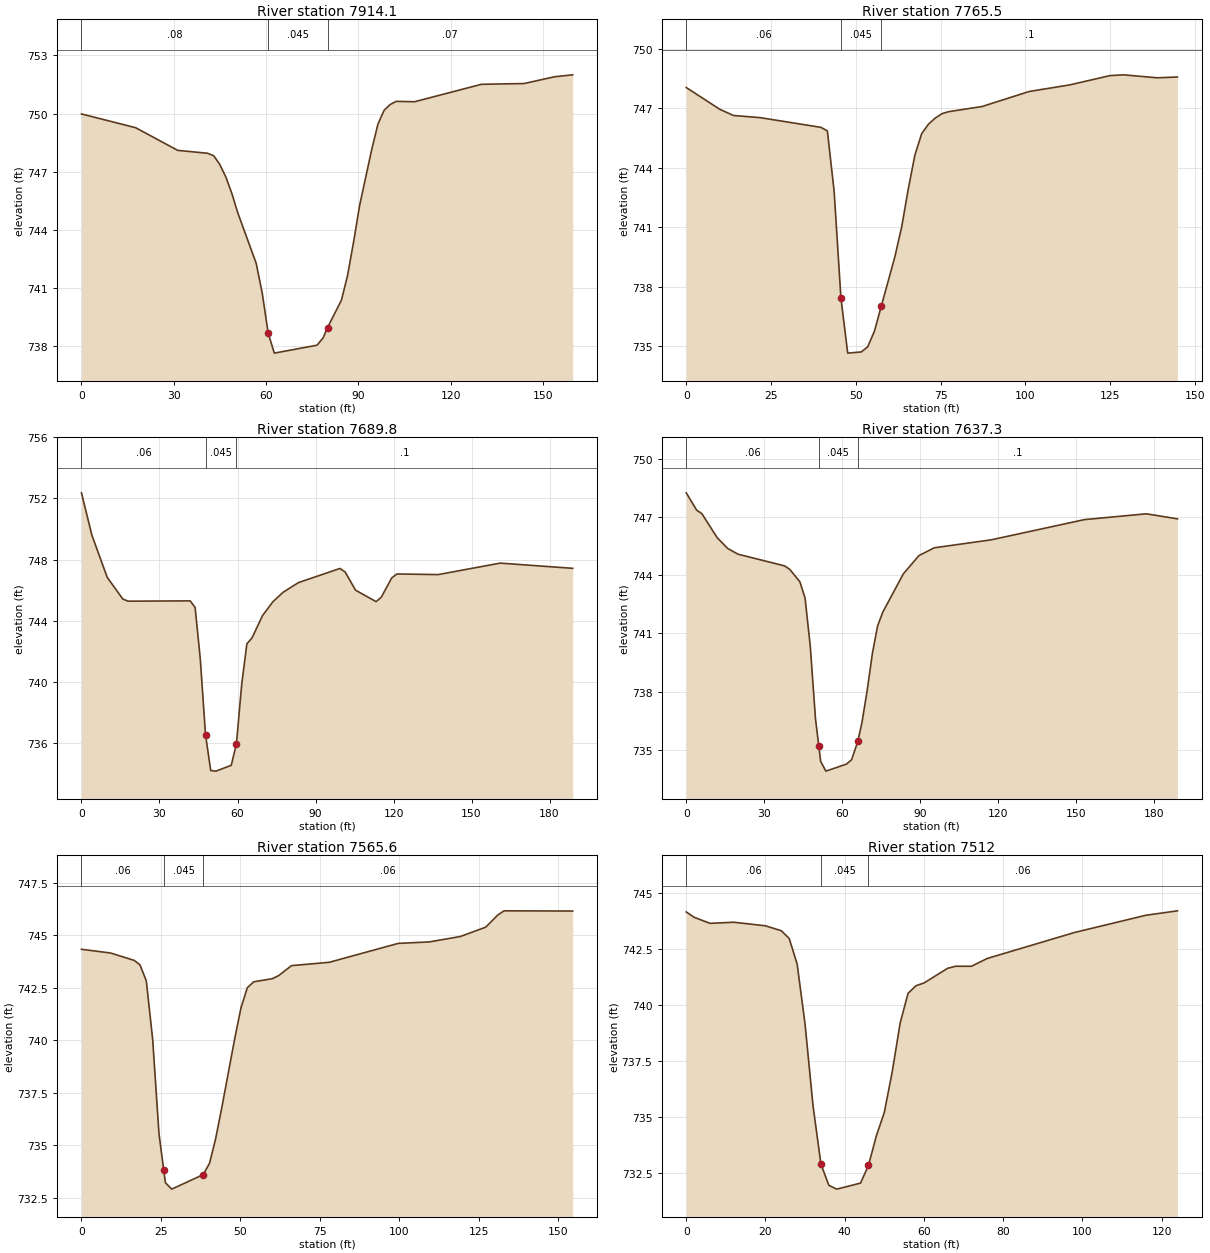
Type RM Length L Ch R = 1 ,7914.1  ,154.6,148.6,140.8
XS GIS Cut Line= 3
     1636114.443      582176.602     1636067.568      582175.734
     1635954.721      582173.997
#Sta/Elev= 30
       0  749.98    17.6  749.27    31.3   748.1      41  747.95      43  747.82
    44.9  747.39    46.9  746.74    48.9  745.87    50.8  744.88    56.8  742.27
    58.8   740.7    60.7  738.66    62.7  737.63    76.6  738.04    78.6  738.43
      80  738.95    84.5  740.36    86.5  741.63    88.5   743.4    90.4  745.23
    94.4  748.17    96.4  749.46    98.4  750.17   100.3  750.46   102.3  750.63
   108.3  750.61     130  751.51   143.9  751.55   153.8   751.9   159.7     752
#Mann= 3 , 0 , 0
       0     .08       0    60.7    .045       0      80     .07       0
Bank Sta=60.7,80
XS Rating Curve= 0 ,0
Exp/Cntr=0.3,0.1

Type RM Length L Ch R = 1 ,7765.5  ,76.3,75.7,75.1
XS GIS Cut Line= 2
     1636103.158      582016.879     1635964.269      582057.678
#Sta/Elev= 29
       0  748.04     9.9  746.94    13.9  746.63    21.8  746.52    39.7  746.03
    41.6  745.85    43.6   742.8    45.6  737.42    47.6  734.64    51.6   734.7
    53.5  734.96    55.5  735.76    57.5  737.01    61.5   739.5    63.5     741
    65.4  742.87    67.4  744.63    69.4  745.71    71.4  746.19    73.4   746.5
    75.4  746.72    77.3  746.82    87.2  747.08   101.1  747.84     113  748.17
   124.9  748.64   128.9  748.68   138.8  748.53   144.8  748.57
#Mann= 3 , 0 , 0
       0     .06       0    45.6    .045       0    57.5      .1       0
Bank Sta=45.6,57.5
XS Rating Curve= 0 ,0
Exp/Cntr=0.3,0.1

Type RM Length L Ch R = 1 ,7689.8  ,52.5,52.5,52.5
XS GIS Cut Line= 2
     1636086.665      581941.359     1635906.978      581999.518
#Sta/Elev= 30
       0  752.37       4   749.6     9.9  746.84    15.9  745.42    17.9  745.28
    41.8   745.3    43.7  744.87    45.7  741.49    47.7  736.54    49.7   734.2
    51.7  734.16    57.6  734.54    59.6  735.96    61.6  739.81    63.6  742.49
    65.6  742.88    69.6  744.33    73.6  745.24    77.5  745.86    83.5   746.5
    99.4  747.42   101.4  747.19   105.4     746   113.3  745.25   115.3  745.54
   119.3   746.8   121.3  747.06   137.2  747.02     161  747.77   188.9  747.43
#Mann= 3 , 0 , 0
       0     .06       0    47.7    .045       0    59.6      .1       0
Bank Sta=47.7,59.6
XS Rating Curve= 0 ,0
Exp/Cntr=0.3,0.1

Type RM Length L Ch R = 1 ,7637.3  ,70.4,71.6,71.5
XS GIS Cut Line= 2
     1636077.117      581889.275     1635897.429      581947.435
#Sta/Elev= 30
       0  748.24       4  747.35       6  747.17    11.9  745.93    15.9  745.38
    19.9  745.08    37.8  744.48    39.8   744.3    43.7  743.66    45.7  742.82
    47.7  740.34    49.7  736.61      51  735.18    51.7  734.41    53.7  733.91
    61.6  734.27    63.6   734.5      66  735.45    67.6  736.43    69.6  738.08
    71.6  739.98    73.6  741.39    75.6   742.1    83.5  744.07    89.5  745.01
    95.4  745.41   117.3  745.82   153.1  746.86   176.9  747.16   188.9   746.9
#Mann= 3 , 0 , 0
       0     .06       0      51    .045       0      66      .1       0
Bank Sta=51,66
XS Rating Curve= 0 ,0
Exp/Cntr=0.3,0.1

Type RM Length L Ch R = 1 ,7565.6  ,56.1,53.6,52.3
XS GIS Cut Line= 4
     1636038.054      581830.247     1636019.825      581832.852
     1635955.589      581853.685     1635889.617      581872.782
#Sta/Elev= 29
       0  744.34     9.2  744.16    16.6  743.81    18.4   743.6    20.4  742.84
    22.4  740.06    24.4  735.55    25.9  733.81    26.4  733.23    28.4  732.92
    38.3  733.61    40.3  734.15    42.2   735.3    44.2  736.83    48.2  740.06
    50.2  741.55    52.2  742.51    54.2  742.79    60.1  742.94    62.1  743.09
    66.1  743.56      78  743.72    99.7  744.62   109.5  744.69   119.3  744.95
   127.2  745.39   131.1  745.98     133  746.17   154.6  746.16
#Mann= 3 , 0 , 0
       0     .06       0    25.9    .045       0    38.3     .06       0
Bank Sta=25.9,38.3
XS Rating Curve= 0 ,0
Exp/Cntr=0.3,0.1

Type RM Length L Ch R = 1 ,7512    ,25.2,25.2,25.3
XS GIS Cut Line= 2
      1636031.11      581770.352     1635915.658      581815.491
#Sta/Elev= 29
       0  744.17       2  743.93       6  743.66      12  743.71      20  743.55
      24  743.33      26  742.98      28  741.84      30  739.14      32  735.51
      34  732.89      36  731.94      38  731.77      44  732.04      46  732.83
      48  734.16      50   735.2      52  737.02      54   739.2      56  740.53
      58  740.87      60  740.99      66  741.65      68  741.74      72  741.74
      76  742.09      98  743.25     116  744.02     124  744.22
#Mann= 3 , 0 , 0
       0     .06       0      34    .045       0      46     .06       0
Bank Sta=34,46
XS Rating Curve= 0 ,0
Exp/Cntr=0.3,0.1

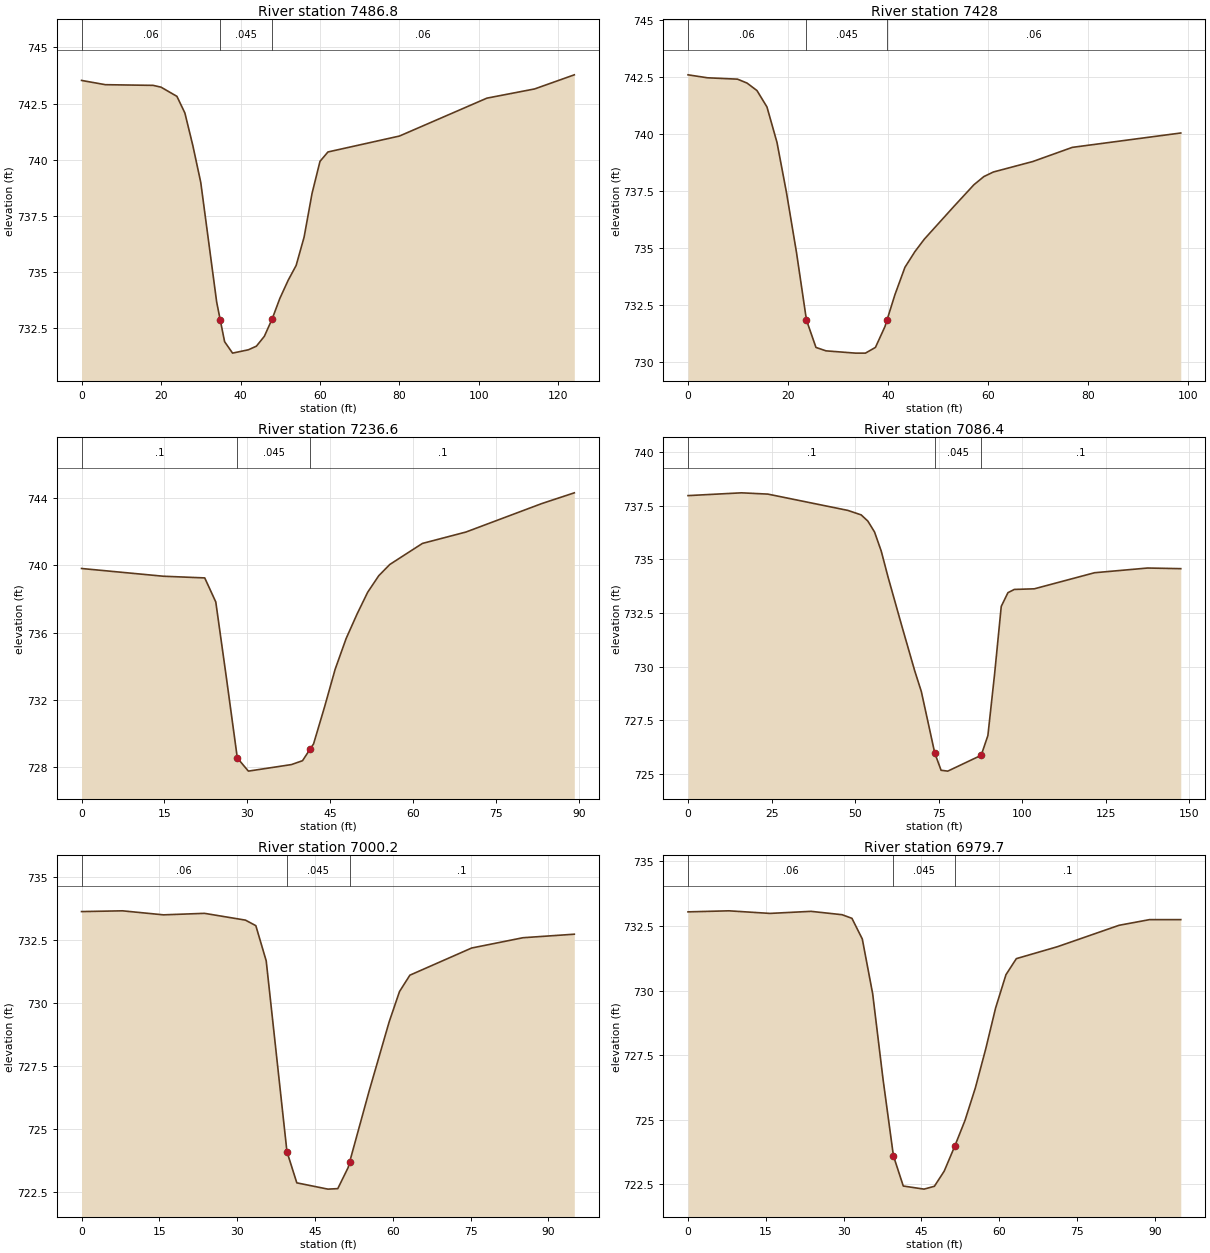
Type RM Length L Ch R = 1 ,7486.8  ,60.7,58.8,56.9
XS GIS Cut Line= 2
     1636024.165      581746.046     1635908.714      581791.185
#Sta/Elev= 27
       0  743.53       6  743.34      18  743.31      20  743.23      24  742.82
      26  742.08      28  740.63      30  738.98      34  733.65    34.9  732.85
      36  731.88      38  731.37      42  731.52      44  731.68      46  732.12
      48  732.91    49.9  733.81      52  734.62      54  735.28      56  736.54
      58  738.49      60  739.92      62  740.34      80  741.05     102  742.74
     114  743.15     124  743.78
#Mann= 3 , 0 , 0
       0     .06       0    34.9    .045       0      48     .06       0
Bank Sta=34.9,48
XS Rating Curve= 0 ,0
Exp/Cntr=0.3,0.1

Type RM Length L Ch R = 1 ,7428    ,191.3,191.4,189.4
XS GIS Cut Line= 2
     1635995.519      581691.359     1635906.978      581734.761
#Sta/Elev= 28
       0   742.6     3.9  742.47     9.9  742.41    11.8  742.24    13.8  741.91
    15.8  741.19    17.8  739.64    19.7  737.44    21.7  734.82    23.7  731.85
    25.6  730.65    27.6   730.5    33.5   730.4    35.5   730.4    37.5  730.65
    39.4  731.56    39.8  731.84    41.4  732.96    43.4  734.16    45.4  734.85
    47.3   735.4    53.2  736.83    57.2  737.78    59.2  738.14    61.1  738.34
      69   738.8    76.9  739.42    98.6  740.05
#Mann= 3 , 0 , 0
       0     .06       0    23.7    .045       0    39.8     .06       0
Bank Sta=23.7,39.8
XS Rating Curve= 0 ,0
Exp/Cntr=0.3,0.1

Type RM Length L Ch R = 1 ,7236.6  ,126.8,150.3,174.9
XS GIS Cut Line= 3
     1635909.582      581522.956     1635890.485        581529.9
     1635831.457      581565.491
#Sta/Elev= 22
       0  739.81    14.8  739.35    22.3  739.25    24.3  737.82    26.2  733.36
    28.2  728.54    30.2  727.76      38  728.15      40  728.38    41.4  729.08
      42  729.38      44  731.59    45.9  733.81    47.9  735.65    49.9  737.12
    51.8   738.4    53.8  739.38    55.8  740.05    61.7   741.3    69.6  741.98
    83.3  743.67    89.2  744.31
#Mann= 3 , 0 , 0
       0      .1       0    28.2    .045       0    41.4      .1       0
Bank Sta=28.2,41.4
XS Rating Curve= 0 ,0
Exp/Cntr=0.3,0.1

Type RM Length L Ch R = 1 ,7086.4  ,104.6,86.2,67.5
XS GIS Cut Line= 3
     1635919.999      581445.699     1635876.596      581407.504
     1635800.207      581360.629
#Sta/Elev= 25
       0  737.98      16  738.11    23.9  738.05    47.8  737.29    51.8  737.08
    53.8  736.79    55.8  736.28    57.8  735.39    59.8   734.2    63.8  731.98
    67.8  729.81    69.8  728.83    73.8  725.97    75.7  725.16    77.7  725.12
    87.7  725.86    89.7  726.78    91.7  729.64    93.7  732.81    95.7  733.45
    97.6   733.6   103.6  733.63   121.6  734.38   137.5   734.6   147.4  734.57
#Mann= 3 , 0 , 0
       0      .1       0    73.8    .045       0    87.7      .1       0
Bank Sta=73.8,87.7
XS Rating Curve= 0 ,0
Exp/Cntr=0.3,0.1

Type RM Length L Ch R = 1 ,7000.2  ,20.4,20.5,20.7
XS GIS Cut Line= 2
     1635938.228      581309.414     1635846.214      581332.852
#Sta/Elev= 20
       0  733.64     7.9  733.67    15.8  733.51    23.7  733.57    31.6   733.3
    33.6  733.08    35.6  731.68    39.6  724.09    41.5  722.85    47.5   722.6
    49.4  722.62    51.4  723.46    51.7  723.69    55.4  726.47    59.3  729.25
    61.3  730.46    63.3  731.11    75.2  732.19    85.1   732.6      95  732.74
#Mann= 3 , 0 , 0
       0     .06       0    39.6    .045       0    51.7      .1       0
Bank Sta=39.6,51.7
XS Rating Curve= 0 ,0
Exp/Cntr=0.3,0.1

Type RM Length L Ch R = 1 ,6979.7  ,33.7,34.3,34.8
XS GIS Cut Line= 2
     1635933.888      581289.449     1635841.874      581312.886
#Sta/Elev= 25
       0  733.05     7.9  733.09    15.8  732.99    23.7  733.07    29.7  732.94
    31.6   732.8    33.6     732    35.6  729.88    37.6  726.57    39.6  723.61
    41.5  722.44    45.5  722.32    47.5  722.43    49.4  723.02    51.4  723.97
    53.4  724.98    55.4  726.24    57.4  727.75    59.3  729.33    61.3  730.62
    63.3  731.24    71.2   731.7    83.1  732.53      89  732.75      95  732.75
#Mann= 3 , 0 , 0
       0     .06       0    39.6    .045       0    51.4      .1       0
Bank Sta=39.6,51.4
XS Rating Curve= 0 ,0
Exp/Cntr=0.3,0.1

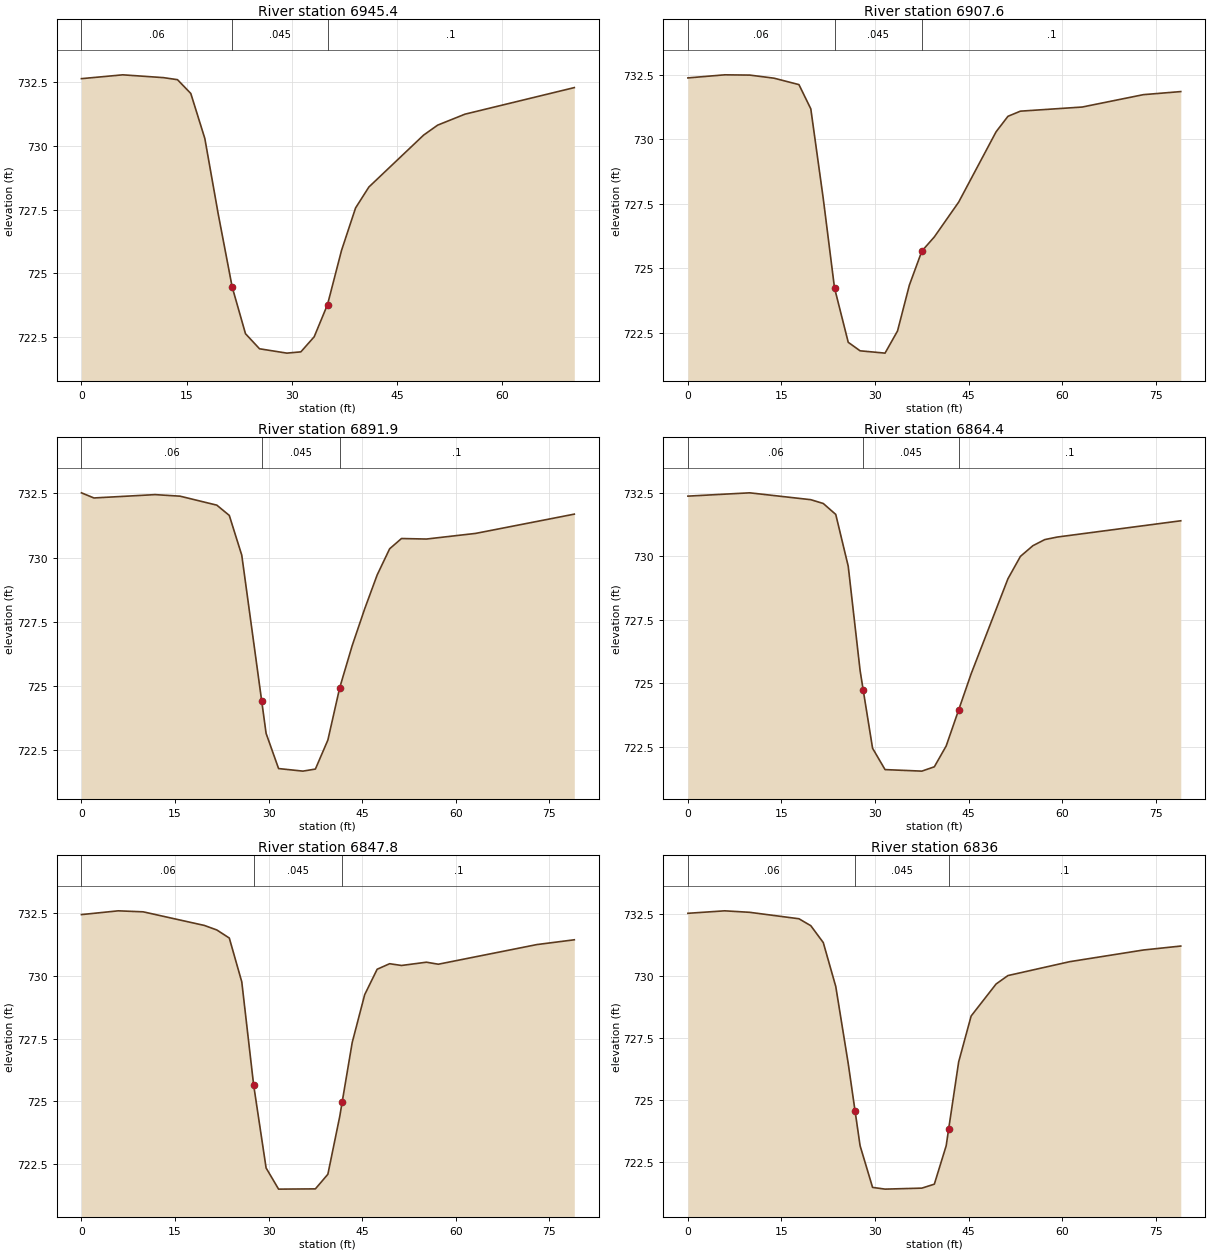
Type RM Length L Ch R = 1 ,6945.4  ,38.5,37.8,37.1
XS GIS Cut Line= 2
      1635910.45      581260.803     1635841.874      581276.428
#Sta/Elev= 21
       0  732.62     5.9  732.77    11.7  732.66    13.7  732.58    15.6  732.04
    17.6  730.28    19.5  727.34    21.5  724.47    23.4  722.64    25.4  722.05
    29.3  721.88    31.3  721.93    33.2  722.52    35.1  723.78    37.1   725.9
    39.1  727.56      41  728.38    48.8  730.41    50.8   730.8    54.7  731.23
    70.3  732.27
#Mann= 3 , 0 , 0
       0     .06       0    21.5    .045       0    35.1      .1       0
Bank Sta=21.5,35.1
XS Rating Curve= 0 ,0
Exp/Cntr=0.3,0.1

Type RM Length L Ch R = 1 ,6907.6  ,15.7,15.7,15.7
XS GIS Cut Line= 2
     1635903.506      581222.609     1635827.117      581242.574
#Sta/Elev= 22
       0  732.38     5.9   732.5     9.9  732.49    13.8  732.37    17.8  732.12
    19.7  731.18    21.7  727.69    23.5  724.23    25.7  722.12    27.6  721.79
    31.6   721.7    33.6  722.56    35.5  724.34    37.5  725.66    39.5  726.21
    43.4  727.56    49.4  730.29    51.3  730.89    53.3  731.09    63.2  731.25
      73  731.73      79  731.85
#Mann= 3 , 0 , 0
       0     .06       0    23.5    .045       0    37.5      .1       0
Bank Sta=23.5,37.5
XS Rating Curve= 0 ,0
Exp/Cntr=0.3,0.1

Type RM Length L Ch R = 1 ,6891.9  ,27.4,27.4,27.4
XS GIS Cut Line= 2
     1635904.374      581206.116     1635827.985      581226.081
#Sta/Elev= 22
       0  732.52       2  732.32    11.8  732.45    15.8  732.39    21.7  732.04
    23.7  731.64    25.7  730.09    28.9   724.4    29.6  723.15    31.6  721.78
    35.5  721.68    37.5  721.76    39.5  722.89    41.4  724.93    43.4  726.57
    45.4     728    47.4  729.32    49.4  730.34    51.3  730.74    55.3  730.72
    63.2  730.94      79  731.69
#Mann= 3 , 0 , 0
       0     .06       0    28.9    .045       0    41.4      .1       0
Bank Sta=28.9,41.4
XS Rating Curve= 0 ,0
Exp/Cntr=0.3,0.1

Type RM Length L Ch R = 1 ,6864.4  ,16.7,16.7,16.7
XS GIS Cut Line= 2
     1635895.693      581180.074     1635819.304      581200.039
#Sta/Elev= 21
       0  732.37     9.9   732.5    19.7  732.23    21.7  732.08    23.7  731.65
    25.7  729.61    27.6  725.51    28.1  724.74    29.6  722.45    31.6  721.61
    37.5  721.55    39.5  721.72    41.4  722.54    43.4  723.96    45.4  725.38
    51.3  729.12    53.3     730    55.3  730.42    57.2  730.66    59.2  730.76
      79   731.4
#Mann= 3 , 0 , 0
       0     .06       0    28.1    .045       0    43.4      .1       0
Bank Sta=28.1,43.4
XS Rating Curve= 0 ,0
Exp/Cntr=0.3,0.1

Type RM Length L Ch R = 1 ,6847.8  ,11.8,11.8,11.8
XS GIS Cut Line= 2
     1635889.617      581164.449     1635813.228      581184.414
#Sta/Elev= 23
       0  732.42     5.9  732.57     9.9  732.53    19.7  731.99    21.7  731.81
    23.7  731.49    25.7  729.75    27.6  725.66    29.6  722.36    31.6  721.52
    37.5  721.53    39.5  722.11    41.4   724.4    41.8  724.99    43.4  727.34
    45.4  729.24    47.4  730.25    49.4  730.47    51.3   730.4    55.3  730.53
    57.2  730.45      73  731.23      79  731.42
#Mann= 3 , 0 , 0
       0     .06       0    27.6    .045       0    41.8      .1       0
Bank Sta=27.6,41.8
XS Rating Curve= 0 ,0
Exp/Cntr=0.3,0.1

Type RM Length L Ch R = 1 ,6836    ,21.8,21.8,21.8
XS GIS Cut Line= 2
     1635886.144      581153.164     1635809.756      581173.129
#Sta/Elev= 23
       0  732.54     5.9  732.64     9.9  732.58    17.8  732.32    19.7  732.04
    21.7  731.36    23.7  729.59    25.7  726.48    26.8  724.56    27.6  723.17
    29.6  721.49    31.6  721.42    37.5  721.46    39.5  721.62    41.4  723.17
    41.8  723.85    43.4  726.55    45.4   728.4    49.4  729.69    51.3  730.03
    61.2  730.59      73  731.06      79  731.22
#Mann= 3 , 0 , 0
       0     .06       0    26.8    .045       0    41.8      .1       0
Bank Sta=26.8,41.8
XS Rating Curve= 0 ,0
Exp/Cntr=0.3,0.1