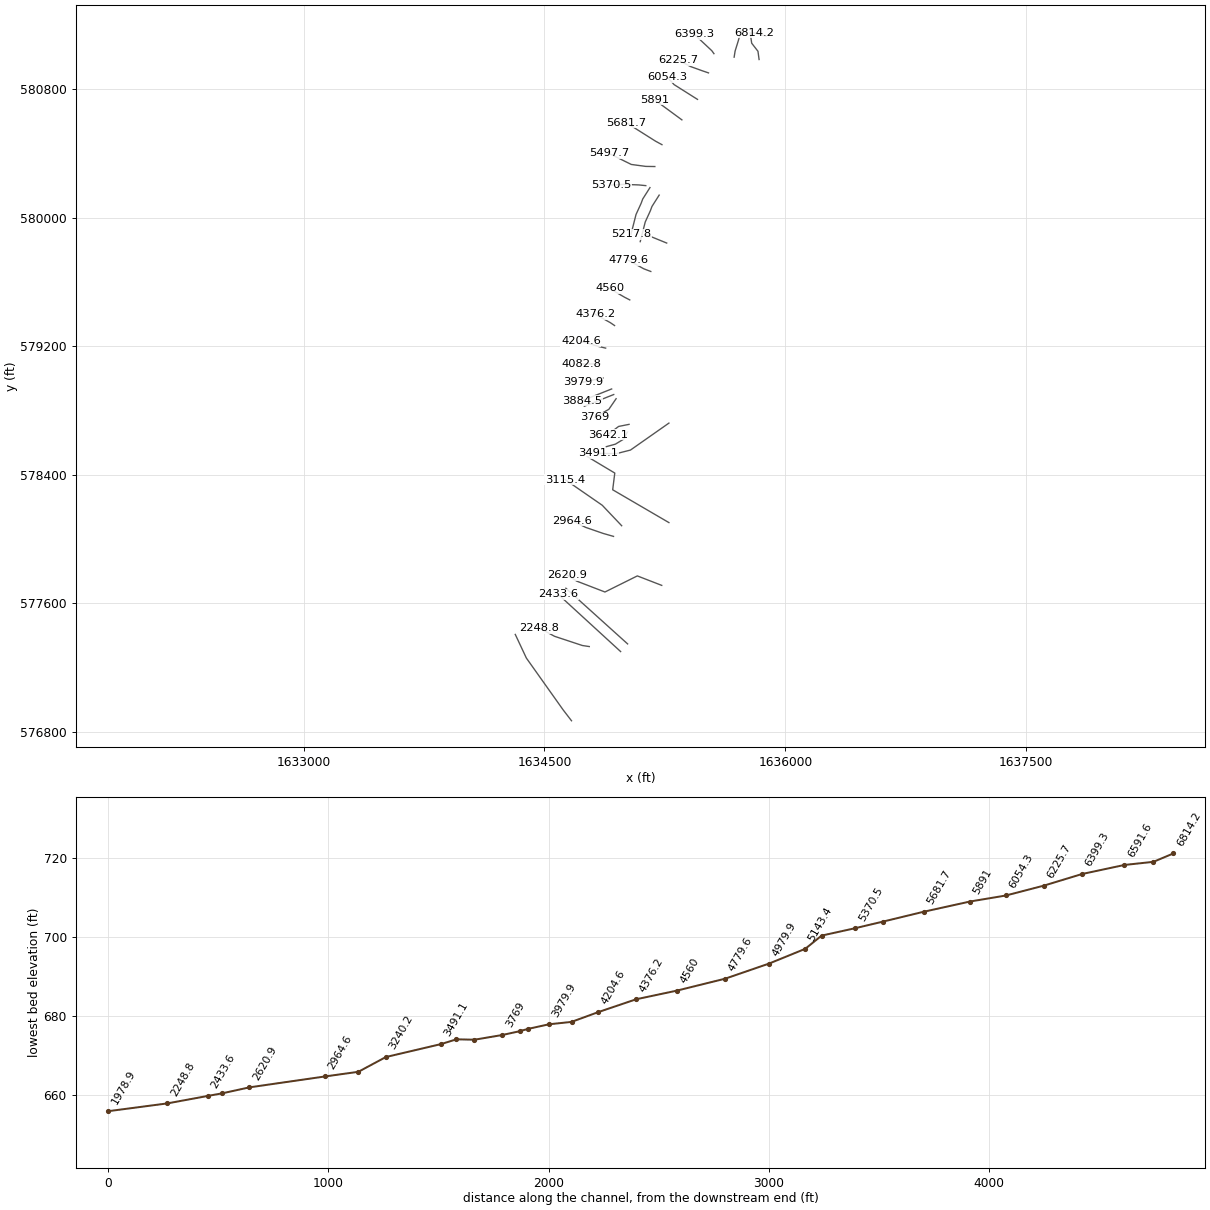
HEC-RAS study LONGRUN.prj: LONGRUN

--- LONGRUN.g01 (geometry) --- (continued)

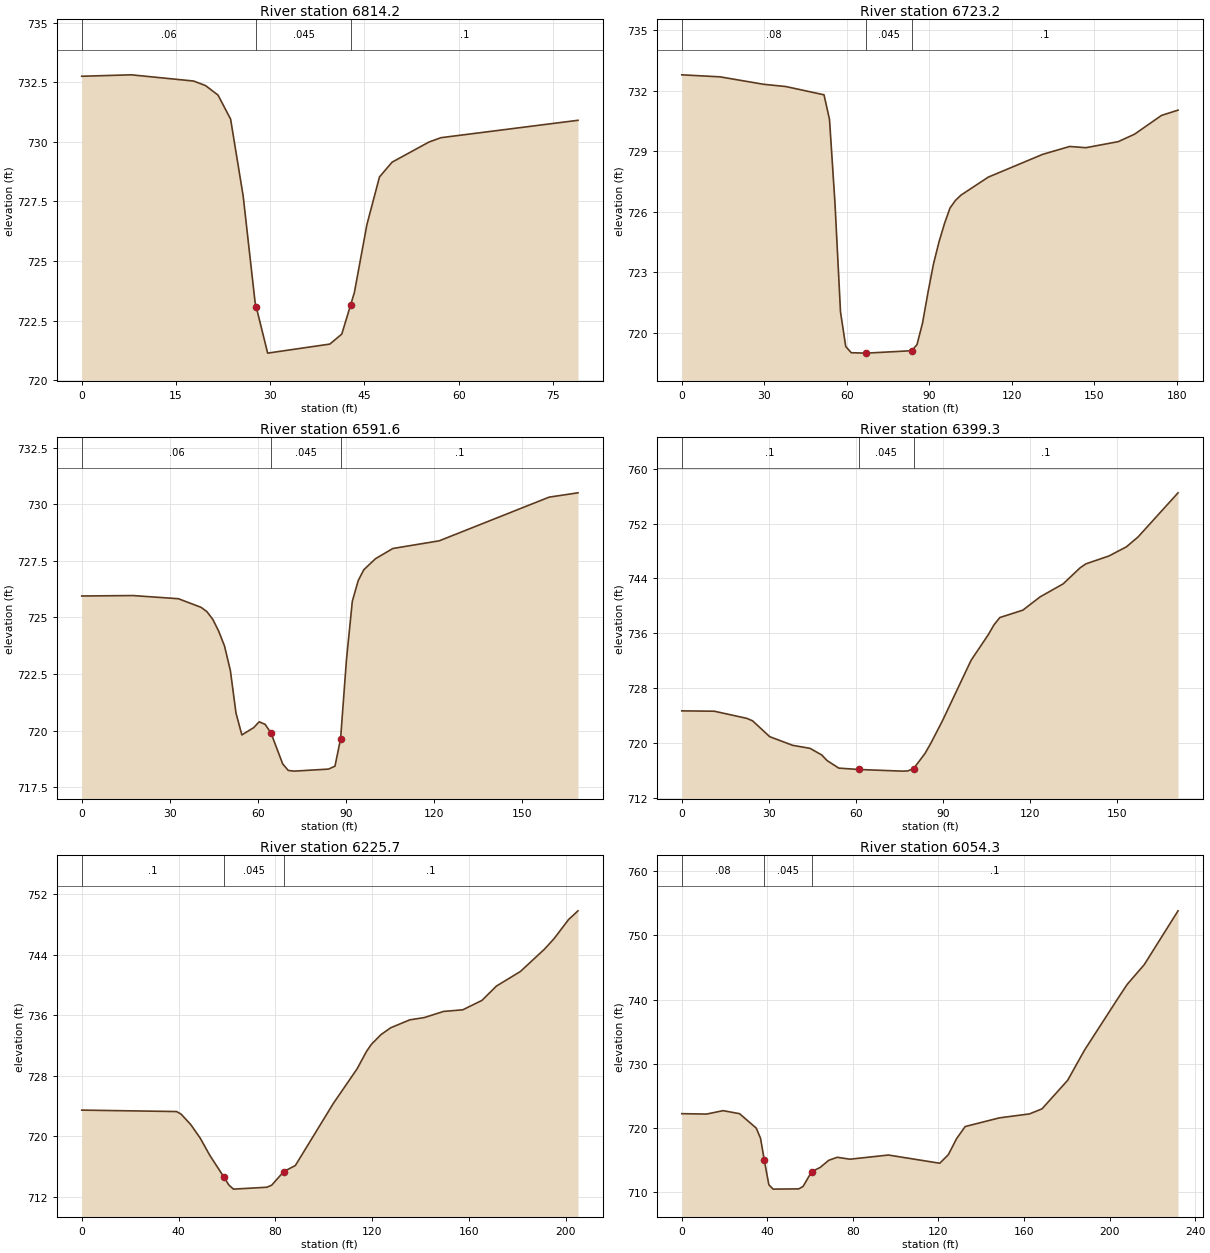
Type RM Length L Ch R = 1 ,6814.2  ,108.9,91,75.3
XS GIS Cut Line= 2
     1635880.068      581132.331     1635803.679      581152.296
#Sta/Elev= 20
       0  732.76     7.9  732.82    17.8  732.56    19.7  732.37    21.7  731.97
    23.7  730.96    25.7  727.73    27.6  723.26    27.8  723.05    29.6  721.13
    39.5  721.51    41.4  721.93    42.8  723.15    43.4  723.67    45.4  726.53
    47.4  728.53    49.4  729.15    55.3     730    57.2  730.18      79  730.91
#Mann= 3 , 0 , 0
       0     .06       0    27.8    .045       0    42.8      .1       0
Bank Sta=27.8,42.8
XS Rating Curve= 0 ,0
Exp/Cntr=0.3,0.1

Type RM Length L Ch R = 1 ,6723.2  ,152,131.7,106.9
XS GIS Cut Line= 4
     1635836.665      580986.497     1635829.721      581037.713
     1635790.658       581088.06      1635781.11      581152.296
#Sta/Elev= 29
       0  732.79    13.9  732.69    29.8  732.32    37.8  732.21    51.7   731.8
    53.7  730.58    55.7  726.41    57.7  721.04    59.6  719.33    61.6  719.02
    67.1     719    83.6  719.12    85.5  719.42    87.5  720.48    89.5  722.01
    91.5  723.42    93.5  724.51    95.5  725.42    97.5  726.19    99.5  726.57
   101.5  726.83   111.4  727.72   131.2  728.85     141  729.24   146.9  729.18
   158.7  729.48   164.6  729.85   174.4  730.78   180.4  731.04
#Mann= 3 , 0 , 0
       0     .08       0    67.1    .045       0    83.6      .1       0
Bank Sta=67.1,83.6
XS Rating Curve= 0 ,0
Exp/Cntr=0.3,0.1

Type RM Length L Ch R = 1 ,6591.6  ,164.1,192.2,218
XS GIS Cut Line= 4
     1635681.283      581001.254      1635687.36      581039.449
     1635707.325      581103.685     1635723.818      581164.449
#Sta/Elev= 30
       0  725.95    17.4  725.97    32.9  725.83    40.6  725.45    42.6  725.26
    44.6  724.92    46.6   724.4    48.6  723.74    50.6  722.65    52.5  720.78
    54.5  719.81    58.5  720.13    60.4  720.39    62.4  720.28    64.4   719.9
    68.4  718.53    70.3  718.24    72.3  718.21      84   718.3    86.2  718.43
    88.1  719.64    90.1  723.13    92.1  725.72    94.1  726.63      96  727.11
     100   727.6   105.9  728.05   121.7  728.39   159.1  730.32   168.9  730.51
#Mann= 3 , 0 , 0
       0     .06       0    64.4    .045       0    88.1      .1       0
Bank Sta=64.4,88.1
XS Rating Curve= 0 ,0
Exp/Cntr=0.3,0.1

Type RM Length L Ch R = 1 ,6399.3  ,166.6,173.7,181.9
XS GIS Cut Line= 3
     1635555.415      581022.956     1635542.394      581041.185
     1635433.888      581142.747
#Sta/Elev= 30
       0   724.7    11.2  724.65    22.4  723.61    24.4  723.25    30.3  720.94
    38.2  719.68    44.2  719.24    48.2  718.28    50.1  717.45    54.1  716.36
    60.9  716.16    75.9  715.92    77.9  715.95    79.9   716.3    83.8  718.49
    85.8  719.97    89.8  723.24    99.7  732.08   105.6  735.79   107.6  737.25
   109.6   738.3   117.5  739.37   123.5  741.32   131.4   743.2   137.3  745.56
   139.3  746.13   147.2  747.27   153.2   748.6   157.2  750.03     171  756.47
#Mann= 3 , 0 , 0
       0      .1       0    60.9    .045       0    79.9      .1       0
Bank Sta=60.9,79.9
XS Rating Curve= 0 ,0
Exp/Cntr=0.3,0.1

Type RM Length L Ch R = 1 ,6225.7  ,175.7,171.4,166.2
XS GIS Cut Line= 4
     1635521.561      580903.164     1635480.763      580917.053
     1635408.714      580943.095     1635333.193      580983.025
#Sta/Elev= 30
       0  723.44    39.2  723.25    41.1   722.9    45.1  721.51      49  719.72
    52.9  717.47    58.8  714.56    60.8  713.53    62.7  712.98    76.5  713.23
    78.5   713.5    83.5   715.3    88.3  716.11     104  724.33   113.8   728.9
   117.7  731.21   119.7  732.14   123.7  733.44   127.7  734.34   135.6  735.39
   141.6  735.69   149.5   736.5   157.5  736.72   165.4  737.96   171.4  739.86
   181.3  741.79   191.2  744.73   195.2  746.13   201.2  748.66   205.1  749.82
#Mann= 3 , 0 , 0
       0      .1       0    58.8    .045       0    83.5      .1       0
Bank Sta=58.8,83.5
XS Rating Curve= 0 ,0
Exp/Cntr=0.3,0.1

Type RM Length L Ch R = 1 ,6054.3  ,164.4,163.3,162.4
XS GIS Cut Line= 4
     1635452.985      580738.234     1635425.207      580755.595
     1635307.151      580830.247     1635267.221      580874.518
#Sta/Elev= 30
       0  722.25    11.6  722.19    19.3  722.72      27  722.25    34.8  720.01
    36.8  718.43    38.6  714.97    40.7  711.18    42.7   710.5    54.7  710.54
    56.7  710.92    60.7  713.21    64.7  713.88    68.7  714.99    72.7  715.46
    78.6  715.16    96.6  715.81   120.6  714.53   124.6  715.86   128.5  718.38
   132.5  720.25   148.5   721.6   162.5  722.21   168.4     723   180.4  727.45
   188.3  732.16   204.2  740.36   208.2  742.37   216.2  745.46     232  753.84
#Mann= 3 , 0 , 0
       0     .08       0    38.6    .045       0    60.7      .1       0
Bank Sta=38.6,60.7
XS Rating Curve= 0 ,0
Exp/Cntr=0.3,0.1

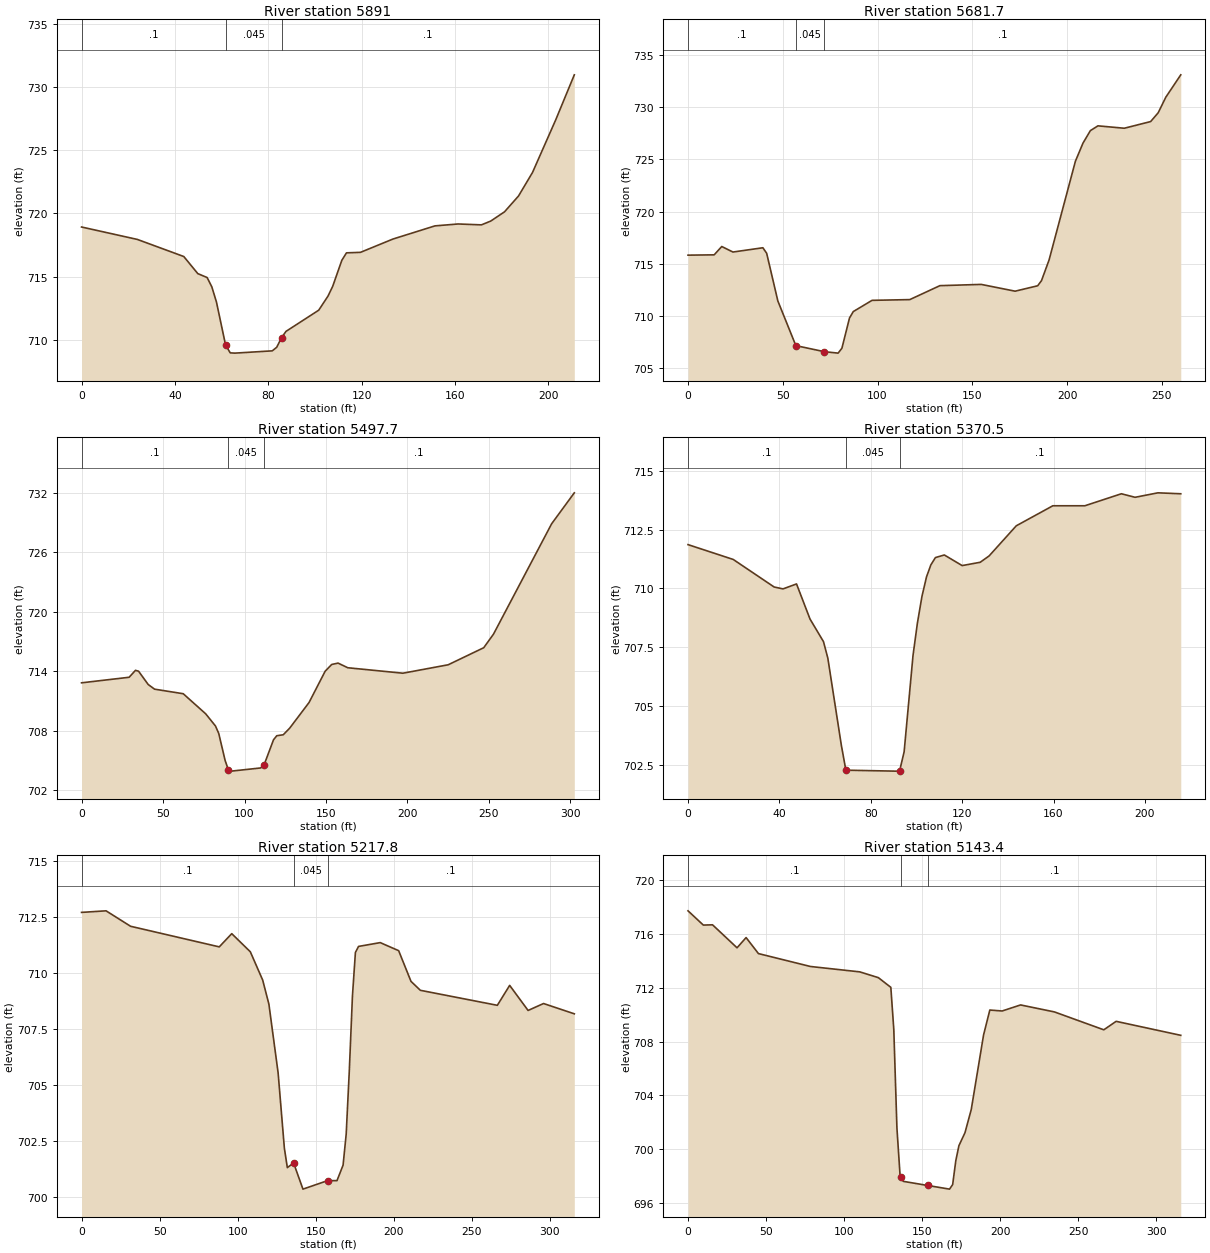
Type RM Length L Ch R = 1 ,5891    ,208,209.3,210.2
XS GIS Cut Line= 2
     1635355.763      580610.629     1635185.624      580735.629
#Sta/Elev= 30
       0  718.93    23.9  717.95    43.8   716.6    49.8  715.25    53.8  714.94
    55.8  714.21    57.8     713    61.7  709.61    63.7  708.99    65.7  708.97
    81.7  709.15    83.6  709.43    85.7   710.2    87.6  710.69   101.6  712.36
   105.6  713.48   107.6  714.25   111.5   716.3   113.5  716.89   119.5  716.93
   133.4  717.98   151.4  719.02   161.3  719.17   171.3   719.1   175.3   719.4
   181.2  720.13   187.2  721.38   193.2  723.24   203.2  727.42   211.1  730.95
#Mann= 3 , 0 , 0
       0      .1       0    61.7    .045       0    85.7      .1       0
Bank Sta=61.7,85.7
XS Rating Curve= 0 ,0
Exp/Cntr=0.3,0.1

Type RM Length L Ch R = 1 ,5681.7  ,174.5,184,194.1
XS GIS Cut Line= 3
     1635231.631      580456.116       1635191.7      580477.817
     1635010.276        580592.4
#Sta/Elev= 30
       0  715.81    13.8  715.84    17.8  716.64    23.7  716.11    39.5  716.52
    41.5  715.99    47.4  711.41    56.9  707.12    71.9  706.54    79.2   706.4
    81.2  706.87    85.2  709.77    87.2  710.39    97.1  711.47     117  711.54
   132.9  712.88   154.7     713   172.6  712.35   184.5  712.87   186.5  713.36
   190.5  715.34   204.4  724.83   208.4  726.57   212.3  727.77   216.3  728.23
   230.2     728   244.1  728.64   248.1  729.49   252.1  730.98     260  733.13
#Mann= 3 , 0 , 0
       0      .1       0    56.9    .045       0    71.9      .1       0
Bank Sta=56.9,71.9
XS Rating Curve= 0 ,0
Exp/Cntr=0.3,0.1

Type RM Length L Ch R = 1 ,5497.7  ,124.7,127.2,128.7
XS GIS Cut Line= 4
      1635187.36      580319.831     1635130.936      580320.699
     1635040.658      580332.852     1634901.769      580401.428
#Sta/Elev= 30
       0  712.83    29.2  713.39    33.1  714.09      35     714    40.9  712.66
    44.8  712.19    62.4  711.73    76.2   709.7    82.2  708.47    84.2  707.72
    88.1     705    90.1  704.05    91.9  703.92   109.9  704.24   111.9   704.5
   117.8  707.08   119.8  707.49   123.8  707.59   127.7  708.25   139.6  710.84
   149.5     714   153.5  714.68   157.4  714.82   163.4  714.35   197.2   713.8
     225  714.65   246.8  716.37   252.8  717.74   288.5  728.88   302.4     732
#Mann= 3 , 0 , 0
       0      .1       0    90.1    .045       0   111.9      .1       0
Bank Sta=90.1,111.9
XS Rating Curve= 0 ,0
Exp/Cntr=0.3,0.1

Type RM Length L Ch R = 1 ,5370.5  ,123,152.8,180
XS GIS Cut Line= 4
     1635130.936      580200.907     1635087.533      580205.247
     1634995.519       580208.72     1634915.658      580204.379
#Sta/Elev= 30
       0  711.86    19.8  711.23    37.7  710.06    41.6  709.98    47.5  710.19
    53.4   708.7    59.3  707.74    61.2  707.04    67.1  703.35    69.1  702.28
    90.6  702.24    92.6  702.24    94.6  703.06    98.5  707.16   100.4  708.52
   102.4  709.66   104.4  710.49   106.3     711   108.3  711.31   112.2  711.42
     120  710.97   127.9  711.11   131.8  711.38   143.7  712.66   159.7  713.51
   173.7  713.51   189.7  714.02   195.7  713.87   205.7  714.06   215.7  714.02
#Mann= 3 , 0 , 0
       0      .1       0    69.1    .045       0    92.6      .1       0
Bank Sta=69.1,92.6
XS Rating Curve= 0 ,0
Exp/Cntr=0.3,0.1

Type RM Length L Ch R = 1 ,5217.8  ,77.6,74.4,74
XS GIS Cut Line= 5
     1635156.978      580188.754     1635111.839      580117.574
      1635102.29      580091.532     1635070.172       580021.22
     1635038.922      579898.824
#Sta/Elev= 30
       0  712.72    15.7  712.79    31.4   712.1    88.2  711.18    96.2  711.77
   108.1  710.96     116   709.7     120  708.62   125.9  705.55   129.9  702.19
   131.8  701.32   135.8  701.53   141.8  700.36   157.6  700.74   163.6  700.74
   167.5  701.43   169.5  702.82   171.5  705.66   173.5  708.98   175.4  710.93
   177.4   711.2   191.3  711.37   203.1  711.01     211  709.64     217  709.24
   266.3  708.57   274.2  709.46     286  708.34   295.9  708.65   315.6  708.19
#Mann= 3 , 0 , 0
       0      .1       0   135.8    .045       0   157.6      .1       0
Bank Sta=135.8,157.6
XS Rating Curve= 0 ,0
Exp/Cntr=0.3,0.1

Type RM Length L Ch R = 1 ,5143.4  ,197.6,163.5,128.1
XS GIS Cut Line= 5
     1635214.269      580141.879     1635169.131      580070.699
     1635159.582      580044.657     1635127.464      579974.345
     1635096.214      579851.949
#Sta/Elev= 30
       0  717.72     9.8  716.66    15.7  716.68    31.4  714.97    37.2  715.73
    45.1  714.54    78.4  713.58     110  713.18   121.9  712.75   129.9  712.03
   131.8  708.89   133.8  701.57   135.8  698.06   136.4  697.92   137.8   697.6
   153.6  697.29   167.5  697.02   169.5  697.36   171.5  699.13   173.5  700.25
   177.4  701.22   181.4  702.94   189.3  708.49   193.3  710.34   201.2  710.27
     213  710.72   234.7   710.2   266.3  708.87   274.2   709.5   315.6  708.46
#Mann= 3 , 0 , 0
       0      .1       0   136.4    .045       0   153.6      .1       0
Bank Sta=136.4,153.6
XS Rating Curve= 0 ,0
Exp/Cntr=0.3,0.1

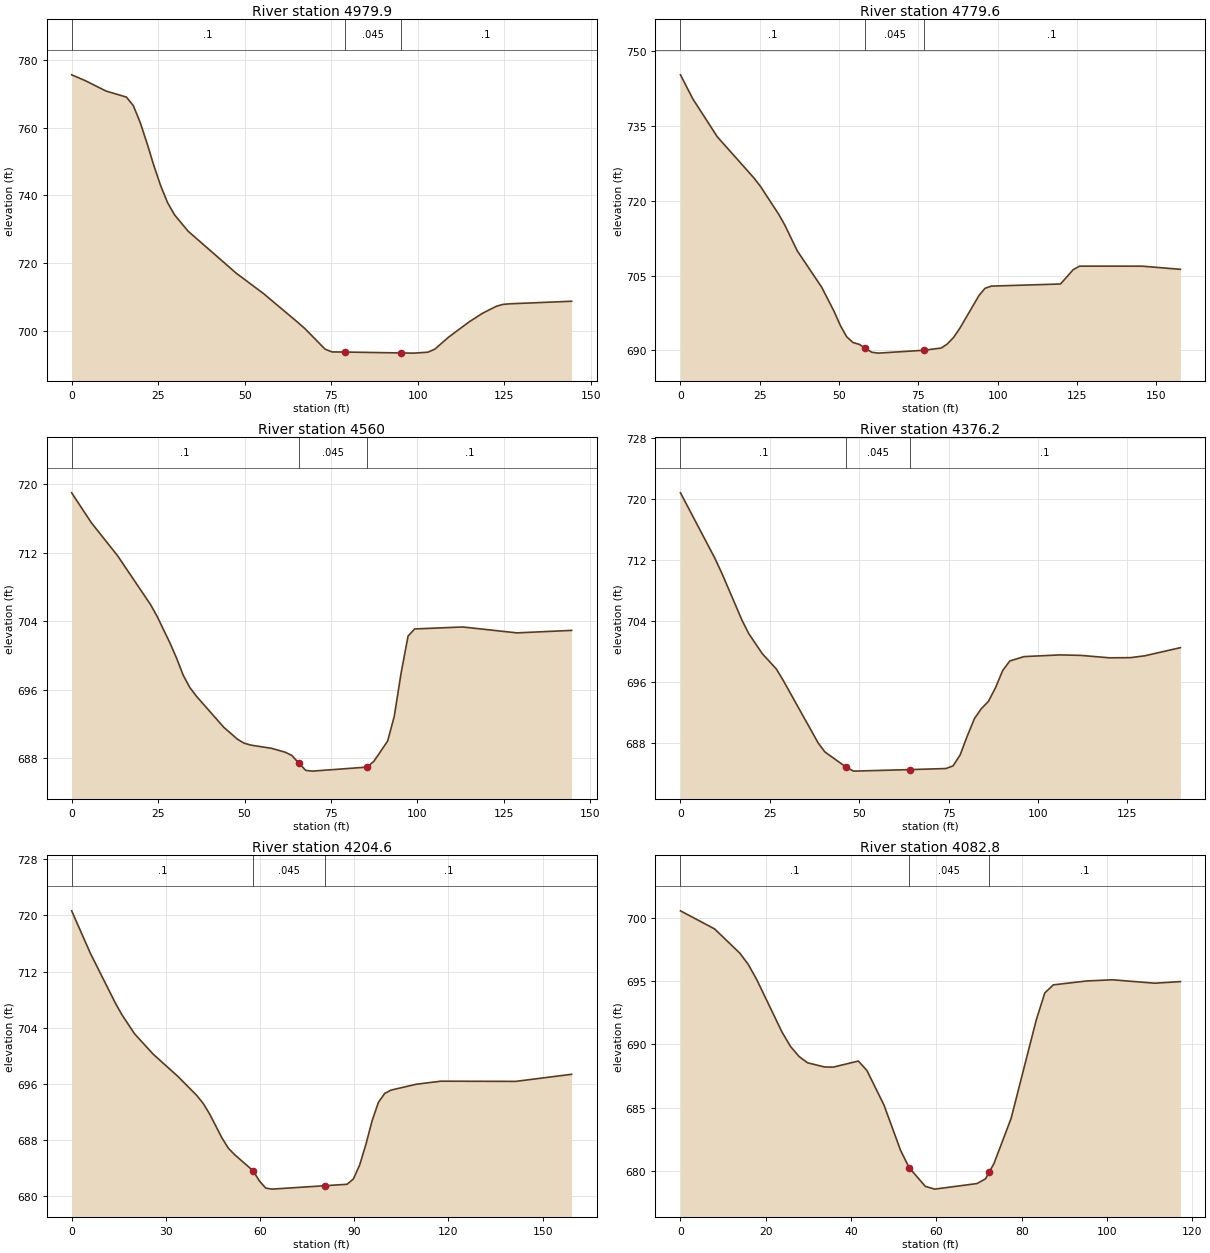
Type RM Length L Ch R = 1 ,4979.9  ,202.9,200.3,197.6
XS GIS Cut Line= 2
     1635261.144      579843.268     1635127.464      579897.956
#Sta/Elev= 30
       0  775.64       4  773.89     9.9  770.85    15.8  769.06    17.8  766.56
    19.8  761.54    21.8  755.29    23.7  748.94    25.7  742.85    27.7  737.84
    29.7  734.24    33.6  729.42    47.5  716.98    55.4  710.94    65.3  702.43
    67.3  700.64    73.2  694.48    75.2  693.67    78.9  693.63      95  693.37
    98.9  693.31   102.9  693.59   104.9  694.48   108.8  697.98   114.8  702.55
   118.7  705.12   122.7  707.18   124.6  707.73   126.6   707.9   144.4  708.66
#Mann= 3 , 0 , 0
       0      .1       0    78.9    .045       0      95      .1       0
Bank Sta=78.9,95
XS Rating Curve= 0 ,0
Exp/Cntr=0.3,0.1

Type RM Length L Ch R = 1 ,4779.6  ,220,219.6,218.9
XS GIS Cut Line= 3
     1635162.186      579666.185     1635118.783      579682.678
     1635021.561      579736.497
#Sta/Elev= 30
       0  745.23     3.9   740.4    11.6  732.82    23.2  724.54    25.2  722.89
      31  717.26    32.9  715.12    36.8  709.98    44.5  702.69    48.4  697.86
    50.4     695    52.4  692.74    54.4  691.59    56.4  691.22    58.3  690.42
    60.3  689.65    62.3  689.47    76.7  690.04    82.2  690.49    84.1   691.3
    86.1  692.62    88.1  694.49    94.1  701.01      96  702.46      98   702.9
   119.8  703.32   123.8  706.19   125.8   706.9   145.6  706.89   157.6  706.26
#Mann= 3 , 0 , 0
       0      .1       0    58.3    .045       0    76.7      .1       0
Bank Sta=58.3,76.7
XS Rating Curve= 0 ,0
Exp/Cntr=0.3,0.1

Type RM Length L Ch R = 1 ,4560    ,183,183.7,183.9
XS GIS Cut Line= 3
      1635031.11      579489.102     1634998.992      579505.595
     1634905.242      579560.282
#Sta/Elev= 30
       0  719.02     5.7  715.52    13.3  711.65    22.8  705.95    24.7  704.58
    28.5  701.39    30.4  699.62    32.3  697.64    34.2  696.22    36.1  695.21
      44  691.58      48  690.17    49.9  689.72    51.9  689.49    57.8  689.12
    61.8  688.66    63.7  688.28    65.7  687.39    67.7  686.54    69.6  686.45
    85.4  686.92    87.4  687.59    91.4  689.98    93.3  692.85    95.3  697.95
    97.3  702.25    99.2  703.09   113.1  703.32   128.8  702.63   144.6  702.92
#Mann= 3 , 0 , 0
       0      .1       0    65.7    .045       0    85.4      .1       0
Bank Sta=65.7,85.4
XS Rating Curve= 0 ,0
Exp/Cntr=0.3,0.1

Type RM Length L Ch R = 1 ,4376.2  ,166.9,171.7,176.8
XS GIS Cut Line= 3
     1634936.492      579329.379     1634909.582      579347.609
     1634815.832      579399.692
#Sta/Elev= 30
       0   720.8     9.6  712.23    11.5  710.32    17.2  704.09    19.1  702.32
    22.9  699.68    26.8  697.69    28.7  696.21    38.5  687.98    40.4  686.79
    46.4  684.78    48.4  684.28    64.2  684.48    74.2  684.62    76.2  684.96
    78.2   686.4    80.2  688.89    82.2  691.17    84.1  692.46    86.1  693.43
    88.1  695.23    90.1  697.48    92.1  698.74    96.1  699.31     106  699.53
   111.9  699.47   119.9  699.15   125.8  699.17   129.8  699.41   139.8  700.48
#Mann= 3 , 0 , 0
       0      .1       0    46.4    .045       0    64.2      .1       0
Bank Sta=46.4,64.2
XS Rating Curve= 0 ,0
Exp/Cntr=0.3,0.1

Type RM Length L Ch R = 1 ,4204.6  ,115,121.8,128.5
XS GIS Cut Line= 4
     1634880.936      579188.754     1634840.138      579198.303
     1634773.297      579218.268      1634727.29      579230.421
#Sta/Elev= 30
       0  720.64       6  714.56      14  707.44      16  705.86      20  703.16
    25.9  700.27    33.9  697.05    39.9  694.34    41.9  693.23    43.9  691.76
    47.9  688.29    49.9  686.87    51.9  685.94    57.8  683.64    59.8  682.19
    61.8  681.19    63.8  681.04    80.8  681.53    87.7  681.73    89.7  682.48
    91.7  684.46    93.7  687.41    95.7  690.81    97.7   693.4    99.7  694.66
   101.7  695.13   109.7  695.96   117.6   696.4   141.4  696.37   159.2  697.38
#Mann= 3 , 0 , 0
       0      .1       0    57.8    .045       0    80.8      .1       0
Bank Sta=57.8,80.8
XS Rating Curve= 0 ,0
Exp/Cntr=0.3,0.1

Type RM Length L Ch R = 1 ,4082.8  ,98.2,102.9,107.2
XS GIS Cut Line= 2
     1634847.082      579090.664     1634729.894      579089.796
#Sta/Elev= 30
       0  700.55       8  699.12    13.9  697.21    15.9  696.31    17.9   695.1
    23.8  690.97    25.8  689.83    27.8  689.04    29.8  688.54    33.8  688.21
    35.8   688.2    41.7  688.68    43.7  687.94    47.7  685.21    51.6  681.62
    53.6  680.26    57.4  678.78    59.6  678.56    69.5     679    71.5  679.37
    72.4  679.92    73.5  680.59    77.5  684.14    83.4  691.92    85.4  694.06
    87.4   694.7    95.3  695.01   101.3   695.1   111.2  694.83   117.2  694.96
#Mann= 3 , 0 , 0
       0      .1       0    53.6    .045       0    72.4      .1       0
Bank Sta=53.6,72.4
XS Rating Curve= 0 ,0
Exp/Cntr=0.3,0.1

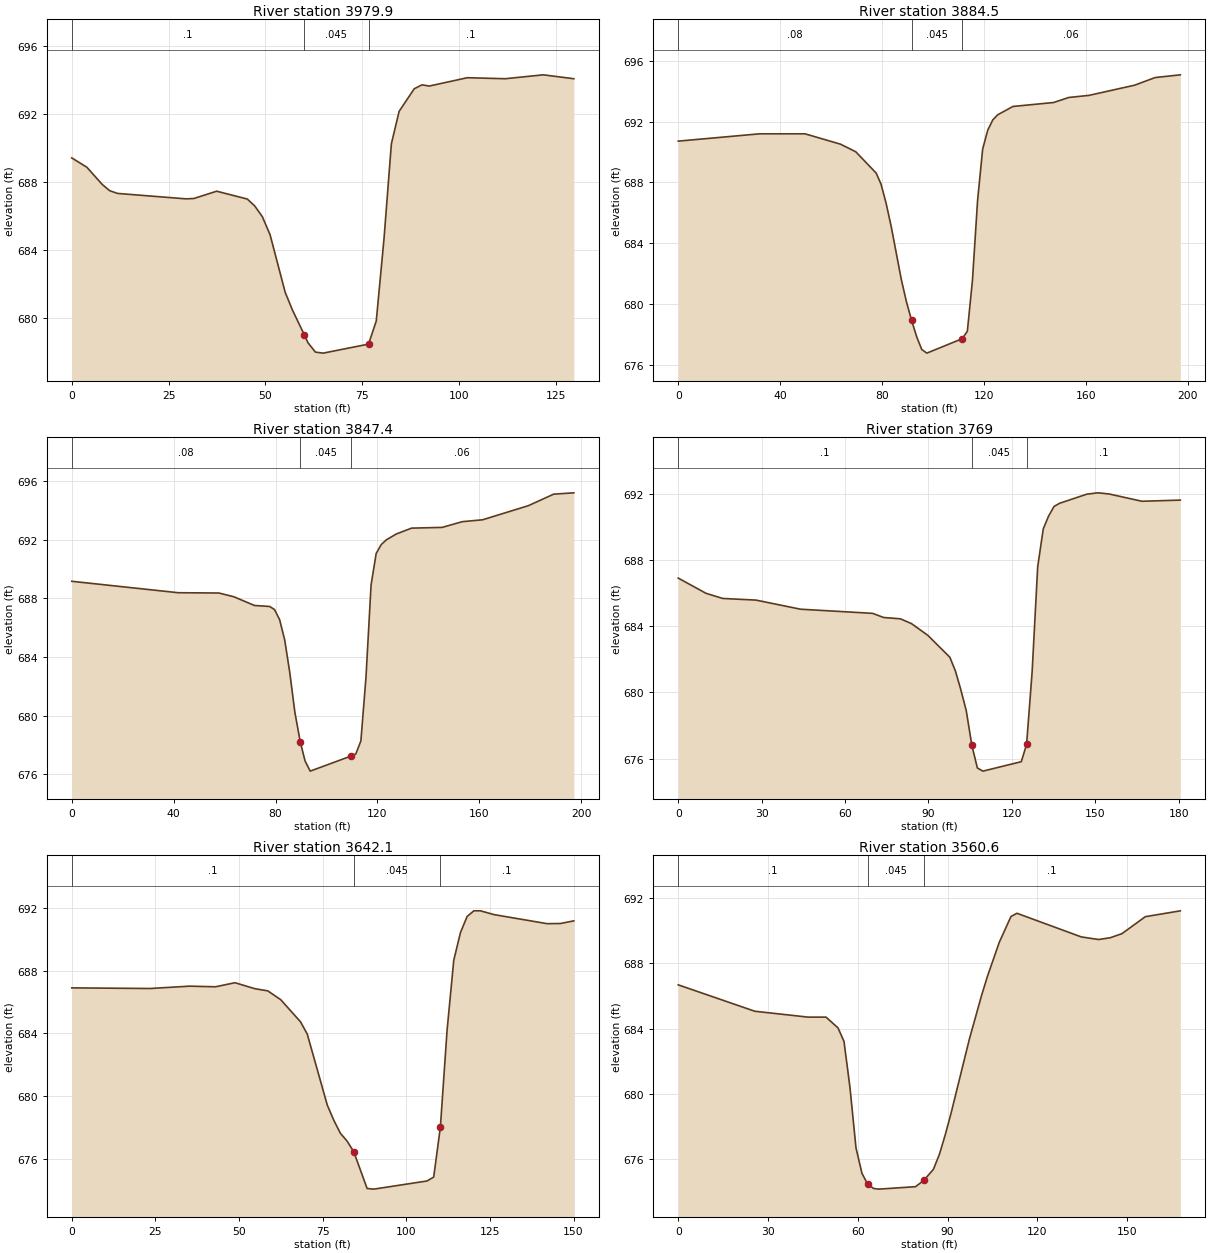
Type RM Length L Ch R = 1 ,3979.9  ,91.4,95.3,99.1
XS GIS Cut Line= 3
     1634864.443      579002.991     1634820.172      578993.442
     1634737.707      578976.081
#Sta/Elev= 30
       0  689.44     3.9  688.89     7.9  687.87     9.8  687.51    11.8  687.35
    29.5  687.03    31.5  687.05    37.4  687.48    45.3  687.02    47.2  686.62
    49.2  685.98    51.2  684.91    55.1  681.52      57  680.47      60  679.04
      61  678.55    62.9  678.01    64.9  677.95    76.6  678.48    78.6  679.84
    80.6  684.69    82.5  690.27    84.5  692.18    88.4  693.51    90.4  693.74
    92.3  693.67   102.1  694.16   111.9   694.1   121.7  694.33   129.6   694.1
#Mann= 3 , 0 , 0
       0      .1       0      60    .045       0    76.6      .1       0
Bank Sta=60,76.6
XS Rating Curve= 0 ,0
Exp/Cntr=0.3,0.1

Type RM Length L Ch R = 1 ,3884.5  ,37.1,37.1,37.1
XS GIS Cut Line= 2
     1634918.263      578934.414     1634735.103      578861.497
#Sta/Elev= 30
       0  690.72    31.9   691.2    49.8   691.2    63.7  690.52    69.7  690.02
    77.7  688.62    79.6   687.9    81.6  686.64    83.6  685.11    87.6   681.6
    89.6  680.15    91.6  678.94    93.6  677.86    95.6  677.02    97.6  676.78
   111.5  677.73   113.5  678.22   115.5  681.56   117.5  686.78   119.5  690.19
   121.5  691.44   123.5  692.12   125.4  692.45   131.4     693   147.4  693.26
   153.3  693.59   161.3  693.73   179.2   694.4   187.2   694.9   197.1  695.08
#Mann= 3 , 0 , 0
       0     .08       0    91.6    .045       0   111.5     .06       0
Bank Sta=91.6,111.5
XS Rating Curve= 0 ,0
Exp/Cntr=0.3,0.1

Type RM Length L Ch R = 1 ,3847.4  ,75.3,78.5,81.4
XS GIS Cut Line= 2
     1634931.283      578899.692     1634748.124      578826.775
#Sta/Elev= 30
       0  689.17    41.8  688.39    57.8  688.37    63.7  688.11    71.7  687.52
    77.7  687.45    79.6  687.24    81.6  686.55    83.6  685.16    85.6  682.92
    87.6  680.21    89.7  678.21    91.6   676.9    93.6  676.21   109.5  677.23
   111.5  677.38   113.5  678.27   115.5  682.62   117.5  688.92   119.5  691.07
   121.5  691.68   123.5     692   127.4   692.4   133.4   692.8   145.4  692.85
   153.3  693.24   161.3  693.37   179.2  694.33   189.2  695.12   197.1  695.21
#Mann= 3 , 0 , 0
       0     .08       0    89.7    .045       0   109.5     .06       0
Bank Sta=89.7,109.5
XS Rating Curve= 0 ,0
Exp/Cntr=0.3,0.1

Type RM Length L Ch R = 1 ,3769    ,123.8,126.9,129.8
XS GIS Cut Line= 3
      1634946.04       578873.65     1634900.901      578807.678
     1634813.228      578758.199
#Sta/Elev= 30
       0  686.91      10  685.99      16  685.68      28  685.58      44  685.03
    69.9  684.78    73.9  684.53    79.9  684.45    83.9  684.16    89.8  683.45
    97.7  682.13    99.7   681.3   101.5  680.26   103.6  678.91   105.6  676.82
   107.6  675.44   109.6  675.25   123.4  675.82   125.3  676.86   127.3  681.25
   129.3  687.59   131.3  689.88   133.2  690.65   135.2  691.24   137.2  691.43
     147  691.98     151  692.06     155  691.99   166.8  691.55   180.6  691.62
#Mann= 3 , 0 , 0
       0      .1       0   105.6    .045       0   125.3      .1       0
Bank Sta=105.6,125.3
XS Rating Curve= 0 ,0
Exp/Cntr=0.3,0.1

Type RM Length L Ch R = 1 ,3642.1  ,83.7,81.5,79.3
XS GIS Cut Line= 3
     1635026.769      578713.928     1634961.665      578700.907
     1634894.825       578650.56
#Sta/Elev= 30
       0  686.91    23.4  686.87    35.2  687.02      43  686.98    48.8  687.24
    54.7  686.86    58.6  686.72    62.5  686.15    68.4  684.74    70.4  683.96
    76.4  679.42    78.4  678.43    80.3  677.63    82.3  677.13    84.3  676.45
    88.3   674.1    90.3  674.06   106.2  674.58   108.2  674.83   110.2  678.02
   112.2   684.2   114.2  688.67   116.2  690.44   118.2  691.47   120.2  691.83
   122.2  691.83   126.2  691.59   142.1  691.01   146.1  691.02   150.1  691.19
#Mann= 3 , 0 , 0
       0      .1       0    84.3    .045       0   110.2      .1       0
Bank Sta=84.3,110.2
XS Rating Curve= 0 ,0
Exp/Cntr=0.3,0.1

Type RM Length L Ch R = 1 ,3560.6  ,76.5,69.5,63
XS GIS Cut Line= 4
     1635015.485      578665.317     1634994.651      578622.782
       1634941.7      578590.664     1634885.276      578575.039
#Sta/Elev= 30
       0  686.69    25.6  685.07    43.4  684.71    49.4  684.71    53.4  684.05
    55.4  683.22    57.4  680.39    59.4   676.7    61.4  675.13    63.3  674.47
    65.3   674.2    67.1  674.16    79.3  674.31    82.1   674.7    85.3  675.38
    87.3   676.3    89.3  677.53    91.3   678.9    97.3  683.36   101.3  685.99
   103.3  687.19   107.3   689.3   111.2  690.88   113.2  691.08   134.7  689.63
   140.5  689.47   144.4  689.58   148.3  689.83   156.1  690.87   167.8  691.23
#Mann= 3 , 0 , 0
       0      .1       0    63.3    .045       0    82.1      .1       0
Bank Sta=63.3,82.1
XS Rating Curve= 0 ,0
Exp/Cntr=0.3,0.1

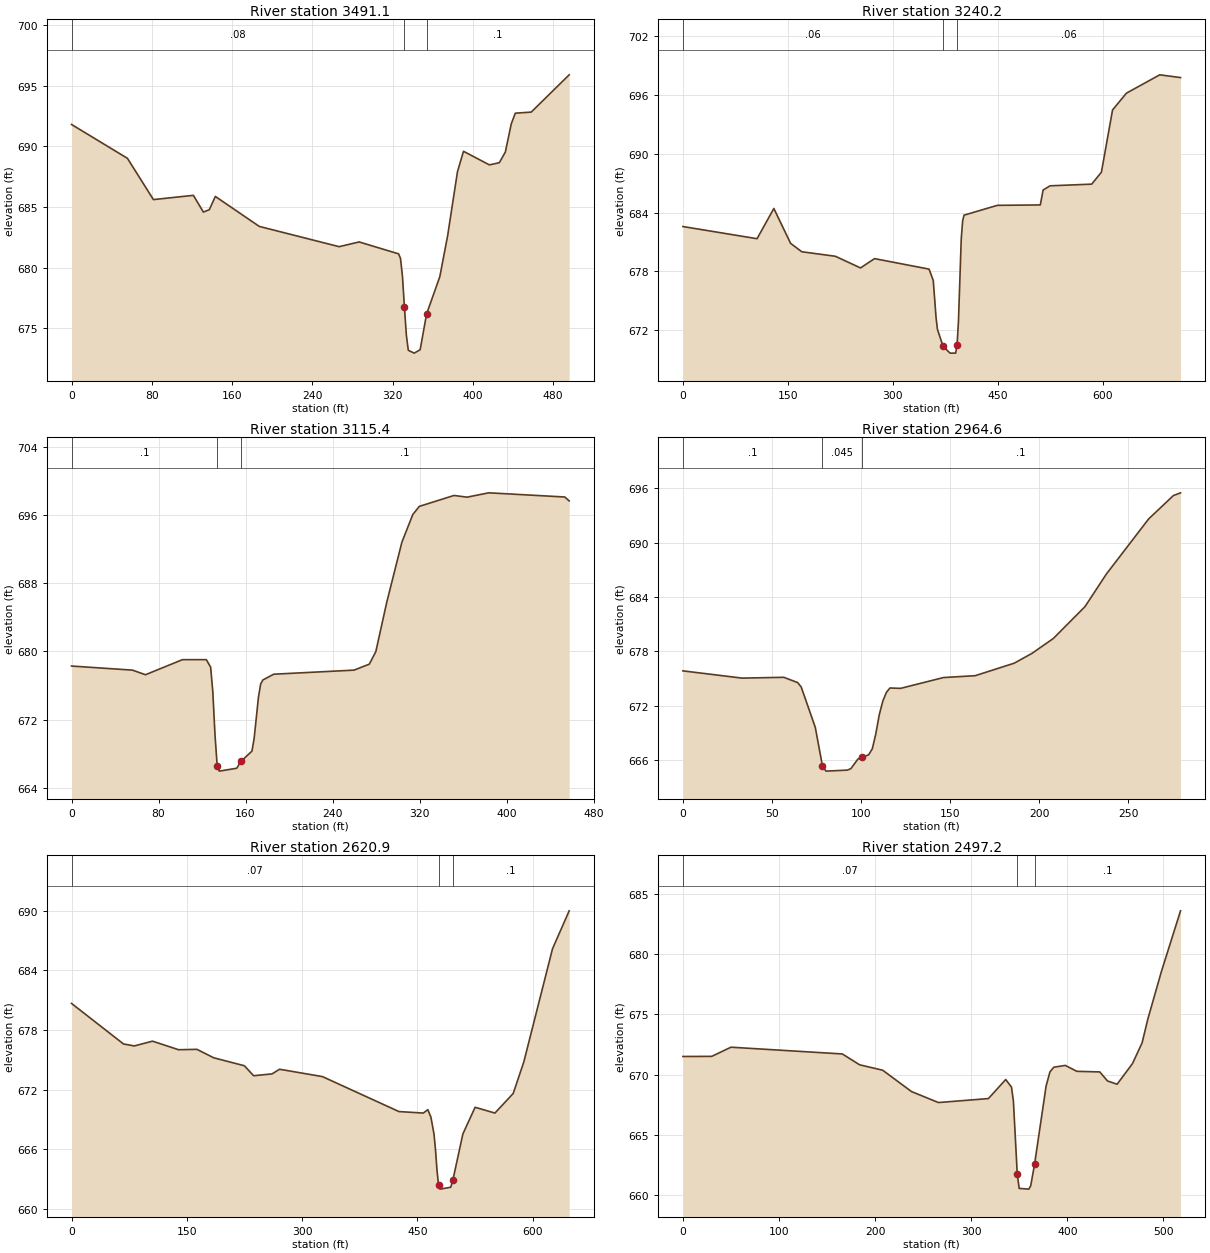
Type RM Length L Ch R = 1 ,3491.1  ,268.5,250.9,126
XS GIS Cut Line= 4
     1635275.033      578721.741      1635035.45      578553.772
      1634948.21      578531.636     1634834.929      578532.938
#Sta/Elev= 30
       0   691.8    55.7  689.01    81.6  685.61   121.4  685.96   131.4  684.58
   137.3  684.78   143.3  685.87   187.1   683.4   266.7  681.73   286.6  682.12
   325.9  681.14   327.8  680.77   329.8  679.26   331.7  676.76   333.7  674.41
   335.6  673.19   341.5  672.96   347.4  673.24   353.8  676.18     367  679.26
   374.8  682.64   384.6  687.91   390.6  689.59   416.4  688.47   426.3  688.65
   432.3  689.53   438.2  691.85   442.2  692.73   458.1  692.82   495.9  695.89
#Mann= 3 , 0 , 0
       0     .08       0   331.7    .045       0   353.8      .1       0
Bank Sta=331.7,353.8
XS Rating Curve= 0 ,0
Exp/Cntr=0.3,0.1

Type RM Length L Ch R = 1 ,3240.2  ,131,124.7,224.9
XS GIS Cut Line= 4
     1635275.033      578101.949     1634924.773      578306.376
     1634937.794      578410.543     1634765.919      578513.407
#Sta/Elev= 30
       0  682.58   105.9  681.34   129.9  684.42   153.8  680.87   169.8  680.01
   217.8  679.55   253.7  678.36   273.7  679.31   351.6  678.24   357.6  677.09
   361.6   673.3   363.6   672.1   371.6  670.37   381.6  669.68   389.6  669.68
   391.6  670.49   393.6  672.95   397.6  681.36   399.6  683.16   401.6  683.74
   449.1  684.74   510.5  684.78   514.5   686.3   524.4  686.73   583.9   686.9
   597.8  688.12   613.7  694.46   633.5  696.17   681.1  698.04   710.8  697.76
#Mann= 3 , 0 , 0
       0     .06       0   371.6    .045       0   391.6     .06       0
Bank Sta=371.6,391.6
XS Rating Curve= 0 ,0
Exp/Cntr=0.3,0.1

Type RM Length L Ch R = 1 ,3115.4  ,139.9,150.9,161.8
XS GIS Cut Line= 3
     1634980.763      578082.418     1634859.669      578210.022
     1634627.898      578370.178
#Sta/Elev= 30
       0  678.29      56  677.81      68  677.27     102  679.04   123.9  679.04
   127.9  678.17   129.9  675.28   131.9  670.25   133.9  666.61   135.9  665.95
   151.9  666.29   155.9  667.11   165.9   668.3   167.9  669.78   171.9  674.66
   173.9  676.18   175.9  676.65   185.9  677.33   259.8  677.81   273.8  678.51
   279.8  679.98   289.8  685.75   303.8  692.84   313.8  696.08   319.8  697.04
   351.7  698.32   363.7  698.12   383.7  698.63   453.6  698.14   457.6  697.68
#Mann= 3 , 0 , 0
       0      .1       0   133.9    .045       0   155.9      .1       0
Bank Sta=133.9,155.9
XS Rating Curve= 0 ,0
Exp/Cntr=0.3,0.1

Type RM Length L Ch R = 1 ,2964.6  ,344.1,343.6,342.4
XS GIS Cut Line= 4
     1634929.981      578016.011     1634866.179      578034.241
     1634756.804      578072.001     1634669.565       578114.97
#Sta/Elev= 30
       0  675.84    33.2  675.04    56.6  675.13    64.4  674.55    66.4  674.06
    74.3  669.61    78.3  665.38    80.3  664.78    92.3  664.89    94.3  665.06
    98.3  666.13   100.3  666.29   104.2  666.57   106.3  667.24   108.2  668.83
   110.2  670.99   112.2   672.5   114.2  673.46   116.2  673.95   122.2  673.91
   146.2   675.1   164.1  675.31     186  676.69     196  677.78   207.9  679.41
   225.7  682.93   237.6   686.5   261.4   692.6   275.3  695.18   279.3  695.48
#Mann= 3 , 0 , 0
       0      .1       0    78.3    .045       0   100.3      .1       0
Bank Sta=78.3,100.3
XS Rating Curve= 0 ,0
Exp/Cntr=0.3,0.1

Type RM Length L Ch R = 1 ,2620.9  ,132.2,123.7,115.4
XS GIS Cut Line= 5
     1635230.328       577710.89     1635078.222      577769.852
     1634876.596      577669.657     1634700.815      577737.366
     1634640.919      577775.126
#Sta/Elev= 30
       0  680.67    67.6   676.6    81.6   676.4   105.4  676.88   139.3  676.02
   163.1  676.06     185  675.21   224.9  674.41   236.9  673.41   260.8  673.59
   270.7  674.06   326.5  673.32     426  669.81   457.7  669.66   463.6     670
   467.6  669.25   471.6  667.56   473.6  665.95   475.5  663.94   477.5  662.47
   479.5  662.02   493.4  662.21   496.2  662.94   509.2  667.56   525.1  670.24
   550.9  669.66   574.7  671.63   588.5   674.8   625.8  686.15   647.5  689.97
#Mann= 3 , 0 , 0
       0     .07       0   477.5    .045       0   496.2      .1       0
Bank Sta=477.5,496.2
XS Rating Curve= 0 ,0
Exp/Cntr=0.3,0.1

Type RM Length L Ch R = 1 ,2497.2  ,63.5,63.6,63.4
XS GIS Cut Line= 2
     1635017.655      577346.306     1634633.106      577693.095
#Sta/Elev= 30
       0  671.51      30  671.52      50  672.28   165.9  671.72   183.9  670.82
   207.9  670.37   237.9   668.6   265.9  667.69   317.9  668.02   335.9   669.6
   341.9  668.97   343.9  667.81   347.9  661.77   349.9  660.57   359.9  660.51
   361.9  660.78     366  662.62   377.9  669.05   381.9  670.23   385.9  670.62
   397.9  670.77   409.9  670.28   433.8  670.23   441.8  669.48   451.8  669.21
   467.8  670.92   477.8  672.64   483.8  674.62   497.8  678.53   517.8  683.59
#Mann= 3 , 0 , 0
       0     .07       0   347.9    .045       0     366      .1       0
Bank Sta=347.9,366
XS Rating Curve= 0 ,0
Exp/Cntr=0.3,0.1

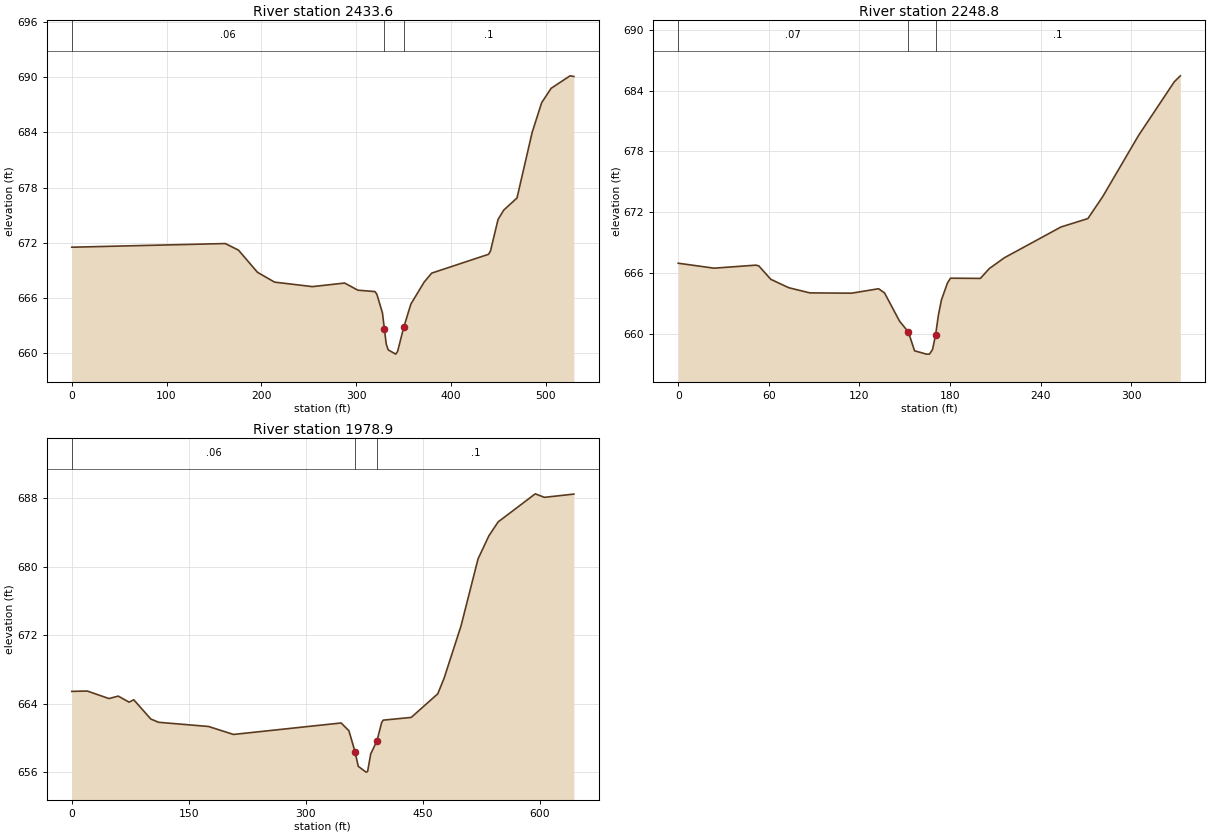
Type RM Length L Ch R = 1 ,2433.6  ,175.3,184.9,194.9
XS GIS Cut Line= 2
     1634974.252      577298.563     1634583.627      577656.636
#Sta/Elev= 30
       0  671.51     162  671.91     176  671.19     196  668.78     214  667.71
     254  667.22     288  667.61     302  666.83     320  666.68     322  666.39
   327.9  664.36   329.9  662.64   331.9  660.97   333.9  660.34   341.9  659.87
   343.9  660.17   350.5  662.84   357.9  665.32   371.9  667.71   379.9  668.69
   439.9  670.74   441.9  671.09   449.9  674.53   455.9  675.55   469.9  676.87
   485.9  684.01   495.9  687.24   505.9  688.81   525.9  690.17   529.9   690.1
#Mann= 3 , 0 , 0
       0     .06       0   329.9    .045       0   350.5      .1       0
Bank Sta=329.9,350.5
XS Rating Curve= 0 ,0
Exp/Cntr=0.3,0.1

Type RM Length L Ch R = 1 ,2248.8  ,284.3,269.9,255.3
XS GIS Cut Line= 4
      1634778.94      577329.813     1634735.971      577336.324
     1634562.794      577393.616     1634469.044      577444.397
#Sta/Elev= 30
       0  666.95    23.7  666.46    51.4  666.76    53.4  666.68    61.3  665.36
    73.2  664.53    87.1  664.02   114.8  663.99   132.7  664.43   136.6  664.02
   146.6  661.22   152.4  660.16   156.5   658.3   164.4  657.97   166.4  657.97
   168.4  658.42   170.4  659.84   172.3  661.82   174.3  663.32   178.3     665
   180.3  665.47   200.1  665.45     206  666.42     216  667.49   253.5  670.53
   271.3  671.36   281.2  673.55   304.8  679.56   328.5  684.87   332.5  685.46
#Mann= 3 , 0 , 0
       0     .07       0   152.4    .045       0   170.4      .1       0
Bank Sta=152.4,170.4
XS Rating Curve= 0 ,0
Exp/Cntr=0.3,0.1

Type RM Length L Ch R = 1 ,1978.9  ,1984.1,1979,1971.3
XS GIS Cut Line= 4
     1634668.263      576867.574     1634616.179      576935.282
     1634387.013      577258.199     1634318.002      577405.334
#Sta/Elev= 30
       0  665.42    19.9  665.46    47.7  664.58    59.6  664.87    73.5  664.16
    79.5  664.44   101.4  662.19   111.4  661.81   175.4  661.32   207.4  660.39
   345.4  661.73   355.4  660.83   363.4  658.34   367.4  656.67   377.4  655.99
   379.4  656.06   383.4  658.12   391.4  659.64   397.4  661.78   399.4  662.06
   435.4  662.38   469.4  665.14   477.4  666.93   499.2  673.06     521  680.88
   534.9  683.58   546.8  685.21   594.4  688.49   606.2  688.08   643.9  688.46
#Mann= 3 , 0 , 0
       0     .06       0   363.4    .045       0   391.4      .1       0
Bank Sta=363.4,391.4
XS Rating Curve= 0 ,0
Exp/Cntr=0.3,0.1

Chan Stop Cuts=-1
Use User Specified Reach Order=0
Composite Channel Slope=5